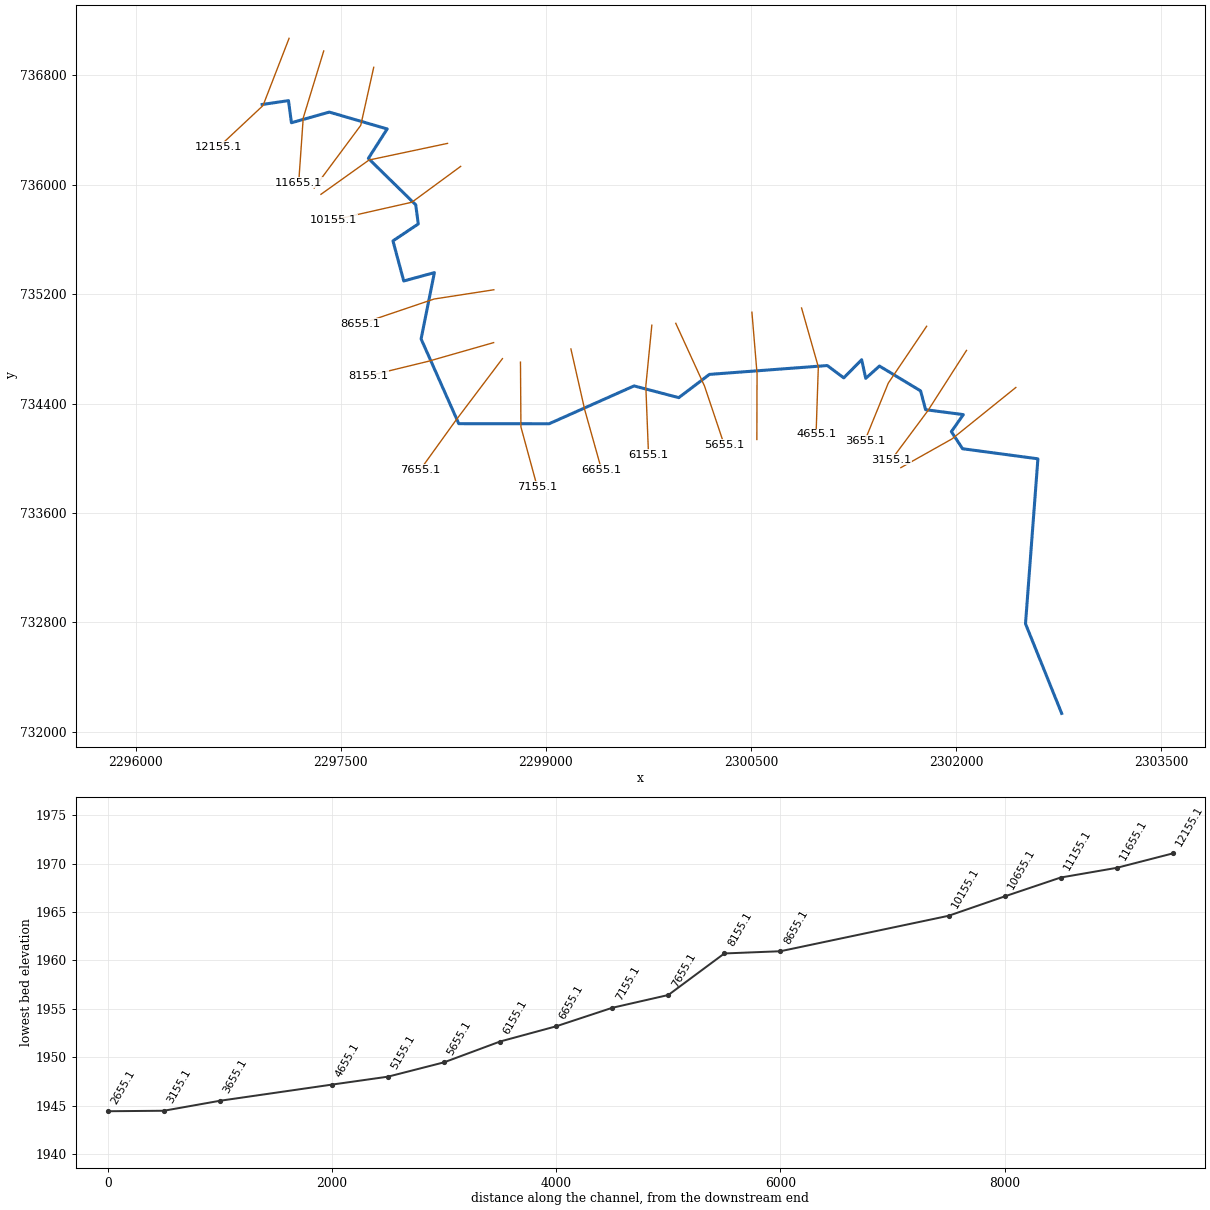
--- DAVISLCK.prj (project) ---

Proj Title=DAVISLCK
Current Plan=p01
Geom File=g01
Flow File=f01
Plan File=p01
DSS Export Rating Curves=0
DSS Export Rating Curve Sorted=0
DSS Export Volume Flow Curves=0
DXF OffsetX=0
DXF OffsetY=0
DXF ScaleX=0
DXF ScaleY=0

--- DAVISLCK.p01 (plan) ---

Plan Title=Floodplain
Program Version=4.00
Geom File=g01
Flow File=f01
K Sum by GR=0
Std Step Tol=0.01
Critical Tol=0.01
Num of Std Step Trials=20
Max Error Tol=0.3
Flow Tol Ratio=0.001
Split Flow NTrial=30
Split Flow Tol=0.02
Split Flow Ratio=0.02
Log Output Level=0
Friction Slope Method=1
Unsteady Friction Slope Method=2
Unsteady Bridges Friction Slope Method=1
Global Log Level=0
CheckData=False
Run HTab=0
Run UNet=0
Run PostProcess=0
UNET Theta=0
UNET Theta Warmup=0
UNET ZTol=0
UNET ZSATol=0
UNET MxIter=0
UNET MaxInSteps=0
UNET DtIC=0
UNET DtMin=0
UNET MaxCRTS=0
UNET WFStab=0
UNET SFStab=0
UNET WFX=0
UNET SFX=0
UNET DSS MLevel=0
UNET DZMax Abort=0
UNET Convert EG Bridges=0
UNET Use Existing IB Tables=0
UNET Froude Limit=0
UNET Froude Power=0
Write IC File=0
Echo Input=False
Echo Output=False
Write Detailed=0

--- DAVISLCK.f01 (steady flow) ---

Flow Title=Flow
Program Version=4.00
Number of Profiles=1
Profile Names=P100yr
River Rch & RM=DAVISLCK,Main      ,12155.1
557.1147
River Rch & RM=DAVISLCK,Main      ,11155.1
560.2699
River Rch & RM=DAVISLCK,Main      ,11155.1
558.6576
River Rch & RM=DAVISLCK,Main      ,10655.1
571.7339
River Rch & RM=DAVISLCK,Main      ,10655.1
570.7217
River Rch & RM=DAVISLCK,Main      ,10155.1
572.8390
River Rch & RM=DAVISLCK,Main      ,8655.1
582.9934
River Rch & RM=DAVISLCK,Main      ,8655.1
583.6440
River Rch & RM=DAVISLCK,Main      ,8655.1
580.6839
River Rch & RM=DAVISLCK,Main      ,8655.1
578.6747
River Rch & RM=DAVISLCK,Main      ,8655.1
579.3653
River Rch & RM=DAVISLCK,Main      ,8155.1
603.8319
River Rch & RM=DAVISLCK,Main      ,8155.1
584.2247
River Rch & RM=DAVISLCK,Main      ,7655.1
612.8223
River Rch & RM=DAVISLCK,Main      ,7655.1
611.5214
River Rch & RM=DAVISLCK,Main      ,7155.1
618.1565
River Rch & RM=DAVISLCK,Main      ,6655.1
623.3877
River Rch & RM=DAVISLCK,Main      ,6655.1
622.0924
River Rch & RM=DAVISLCK,Main      ,6155.1
629.2618
River Rch & RM=DAVISLCK,Main      ,6155.1
625.7405
River Rch & RM=DAVISLCK,Main      ,5655.1
630.2799
River Rch & RM=DAVISLCK,Main      ,5155.1
638.5773
River Rch & RM=DAVISLCK,Main      ,5155.1
635.6603
River Rch & RM=DAVISLCK,Main      ,4655.1
701.9671
River Rch & RM=DAVISLCK,Main      ,4655.1
700.1178
River Rch & RM=DAVISLCK,Main      ,3655.1
707.3086
River Rch & RM=DAVISLCK,Main      ,3655.1
706.7403
River Rch & RM=DAVISLCK,Main      ,3655.1
705.5440
River Rch & RM=DAVISLCK,Main      ,3155.1
709.5884
River Rch & RM=DAVISLCK,Main      ,3155.1
708.6590
River Rch & RM=DAVISLCK,Main      ,2655.1
711.4906
Boundary for River Rch & Prof#=DAVISLCK,Main      ,1
Up Type=0
Dn Type=3
Dn Slope=0.001272

--- DAVISLCK.g01 (geometry) ---

Geom Title=Geometry
Program Version=4.00

River Reach=DAVISLCK     ,Main
Reach XY= 30
     2296924.540      736586.887     2297117.072      736615.152
     2297138.932      736453.452     2297415.510      736531.297
     2297838.829      736408.128     2297701.270      736192.791
     2298047.787      735853.271     2298066.138      735713.403
     2297881.135      735589.631     2297959.996      735296.641
     2298184.048      735357.609     2298086.919      734872.624
     2298362.385      734253.172     2299023.123      734252.727
     2299644.079      734529.362     2299970.954      734443.573
     2300195.197      734613.589     2301057.195      734678.286
     2301177.333      734588.230     2301308.071      734720.740
     2301337.978      734584.666     2301438.427      734674.526
     2301739.308      734492.933     2301775.609      734355.441
     2302051.593      734319.554     2301963.930      734194.767
     2302046.247      734070.023     2302596.823      733996.344
     2302506.135      732790.672     2302770.586      732135.188

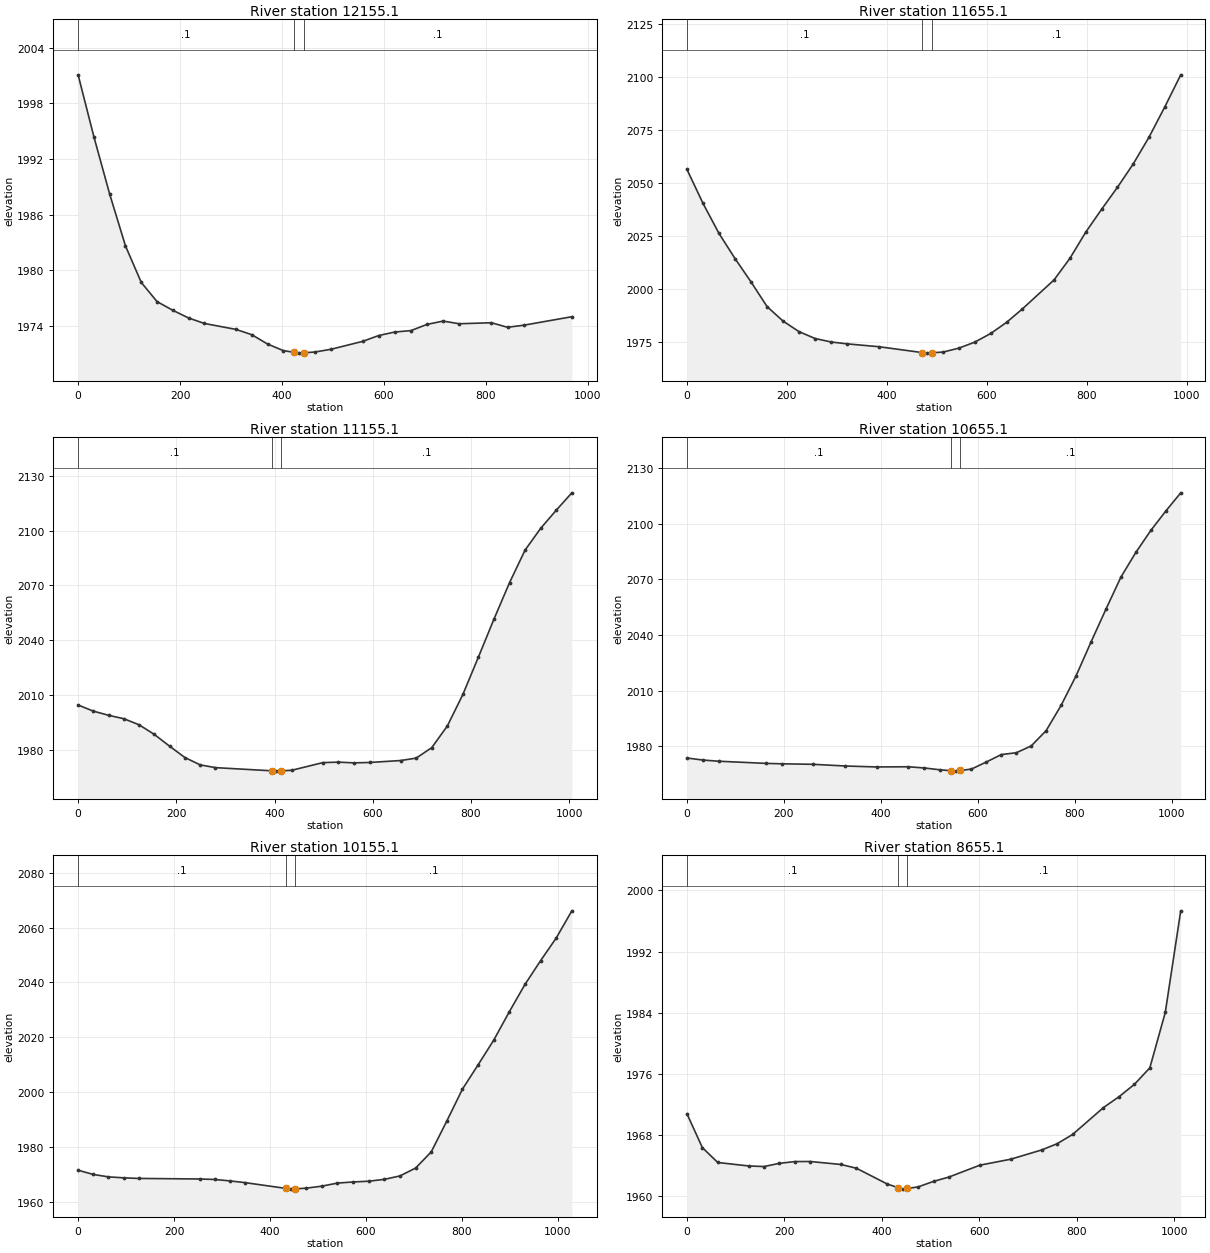
Type RM Length L Ch R = 1 ,12155.1,494.1,500,514.3
XS GIS Cut Line= 3
     2297121.563      737070.621     2296931.106      736579.345
     2296608.349      736277.050
#Sta/Elev= 29
       0 2001.09    31.0 1994.40    62.0 1988.21    93.0 1982.62   124.0 1978.68
   155.0 1976.61   186.0 1975.67   217.0 1974.84   248.0 1974.25   309.9 1973.61
   340.9 1973.04   371.9 1972.03   402.9 1971.32   423.9 1971.14   433.9 1971.05
   443.9 1971.09   464.9 1971.17   495.9 1971.46   558.5 1972.32   590.1 1972.95
   621.7 1973.33   653.2 1973.48   684.8 1974.15   716.4 1974.51   748.0 1974.22
   811.2 1974.33   842.8 1973.84   874.4 1974.06   969.1 1974.98
#Mann= 3 , 0 , 0
       0     0.1       0   423.9   0.045       0   443.9     0.1       0
Bank Sta=423.9,443.9
Exp/Cntr=0.3,0.1

Type RM Length L Ch R = 1 ,11655.1,494.7,500,477.4
XS GIS Cut Line= 3
     2297375.062      736978.566     2297225.061      736488.416
     2297191.812      736014.509
#Sta/Elev= 30
       0 2056.40    32.0 2040.39    64.1 2026.13    96.1 2014.28   128.2 2003.19
   160.2 1991.57   192.2 1984.70   224.3 1979.70   256.3 1976.47   288.3 1974.83
   320.4 1973.94   384.4 1972.58   470.6 1969.82   480.6 1969.56   490.6 1969.72
   512.6 1970.08   544.3 1971.95   575.9 1974.78   607.6 1978.85   639.3 1984.10
   671.0 1990.47   734.3 2004.18   766.0 2014.37   797.6 2026.72   829.3 2037.53
   861.0 2047.92   892.6 2058.97   924.3 2071.68   956.0 2086.05   987.7 2101.14
#Mann= 3 , 0 , 0
       0     0.1       0   470.6   0.045       0   490.6     0.1       0
Bank Sta=470.6,490.6
Exp/Cntr=0.3,0.1

Type RM Length L Ch R = 1 ,11155.1,528.9,500,491.1
XS GIS Cut Line= 3
     2297740.532      736858.763     2297645.580      736434.292
     2297305.458      735976.344
#Sta/Elev= 30
       0 2004.67    31.1 2001.33    62.1 1999.06    93.2 1997.18   124.3 1993.86
   155.3 1988.59   186.4 1982.16   217.5 1975.98   248.6 1971.98   279.6 1970.47
   393.9 1968.74   403.9 1968.56   413.9 1968.71   435.0 1969.02   498.3 1973.21
   530.0 1973.47   561.7 1973.07   593.4 1973.28   656.8 1974.35   688.5 1975.67
   720.2 1981.41   751.9 1993.24   783.6 2010.50   815.2 2030.90   846.9 2051.66
   878.6 2071.56   910.3 2089.36   942.0 2101.21   973.7 2111.11  1005.4 2120.58
#Mann= 3 , 0 , 0
       0     0.1       0   393.9   0.045       0   413.9     0.1       0
Bank Sta=393.9,413.9
Exp/Cntr=0.3,0.1

Type RM Length L Ch R = 1 ,10655.1,478.6,500,484.1
XS GIS Cut Line= 3
     2298280.332      736302.528     2297706.254      736180.950
     2297354.700      735930.155
#Sta/Elev= 29
       0 1973.69    32.6 1972.58    65.2 1971.95   163.0 1970.78   195.6 1970.56
   260.8 1970.28   326.0 1969.38   391.2 1968.86   456.4 1968.96   489.0 1968.32
   521.6 1967.34   544.2 1966.83   554.2 1966.61   564.2 1966.95   586.8 1967.71
   617.7 1971.54   648.5 1975.54   679.4 1976.51   710.2 1980.19   741.0 1988.45
   771.9 2002.08   802.7 2017.96   833.6 2036.22   864.4 2053.91   895.3 2071.20
   926.1 2084.50   957.0 2096.33   987.8 2106.75  1018.6 2116.56
#Mann= 3 , 0 , 0
       0     0.1       0   544.2   0.045       0   564.2     0.1       0
Bank Sta=544.2,564.2
Exp/Cntr=0.3,0.1

Type RM Length L Ch R = 1 ,10155.1,1479.4,1500,1490.1
XS GIS Cut Line= 3
     2298376.252      736134.406     2298019.327      735872.270
     2297447.691      735742.936
#Sta/Elev= 30
       0 1971.51    31.6 1969.96    63.3 1969.08    94.9 1968.73   126.5 1968.51
   253.0 1968.31   284.7 1968.13   316.3 1967.61   348.0 1966.98   432.8 1964.88
   442.8 1964.61   452.8 1964.72   475.4 1964.96   508.0 1965.69   540.5 1966.82
   573.1 1967.22   605.6 1967.50   638.2 1968.18   670.8 1969.43   703.3 1972.30
   735.9 1978.19   768.4 1989.48   801.0 2001.11   833.6 2009.97   866.1 2018.95
   898.7 2029.35   931.2 2039.28   963.8 2047.96   996.4 2056.24  1028.9 2066.13
#Mann= 3 , 0 , 0
       0     0.1       0   432.8   0.045       0   452.8     0.1       0
Bank Sta=432.8,452.8
Exp/Cntr=0.3,0.1

Type RM Length L Ch R = 1 ,8655.1,495.6,500,497
XS GIS Cut Line= 3
     2298618.734      735232.245     2298181.438      735164.568
     2297640.896      734981.577
#Sta/Elev= 28
       0 1970.79    31.6 1966.37    63.2 1964.43   126.4 1963.98   158.0 1963.90
   189.6 1964.32   221.2 1964.55   252.9 1964.56   316.1 1964.17   347.7 1963.68
   410.9 1961.62   432.5 1961.16   442.5 1960.95   452.5 1961.04   474.2 1961.24
   505.9 1961.96   537.6 1962.53   601.0 1964.08   664.4 1964.86   727.8 1966.07
   759.5 1966.88   791.2 1968.09   854.7 1971.61   886.4 1973.02   918.1 1974.64
   949.8 1976.80   981.5 1984.04  1013.2 1997.32
#Mann= 3 , 0 , 0
       0     0.1       0   432.5   0.045       0   452.5     0.1       0
Bank Sta=432.5,452.5
Exp/Cntr=0.3,0.1

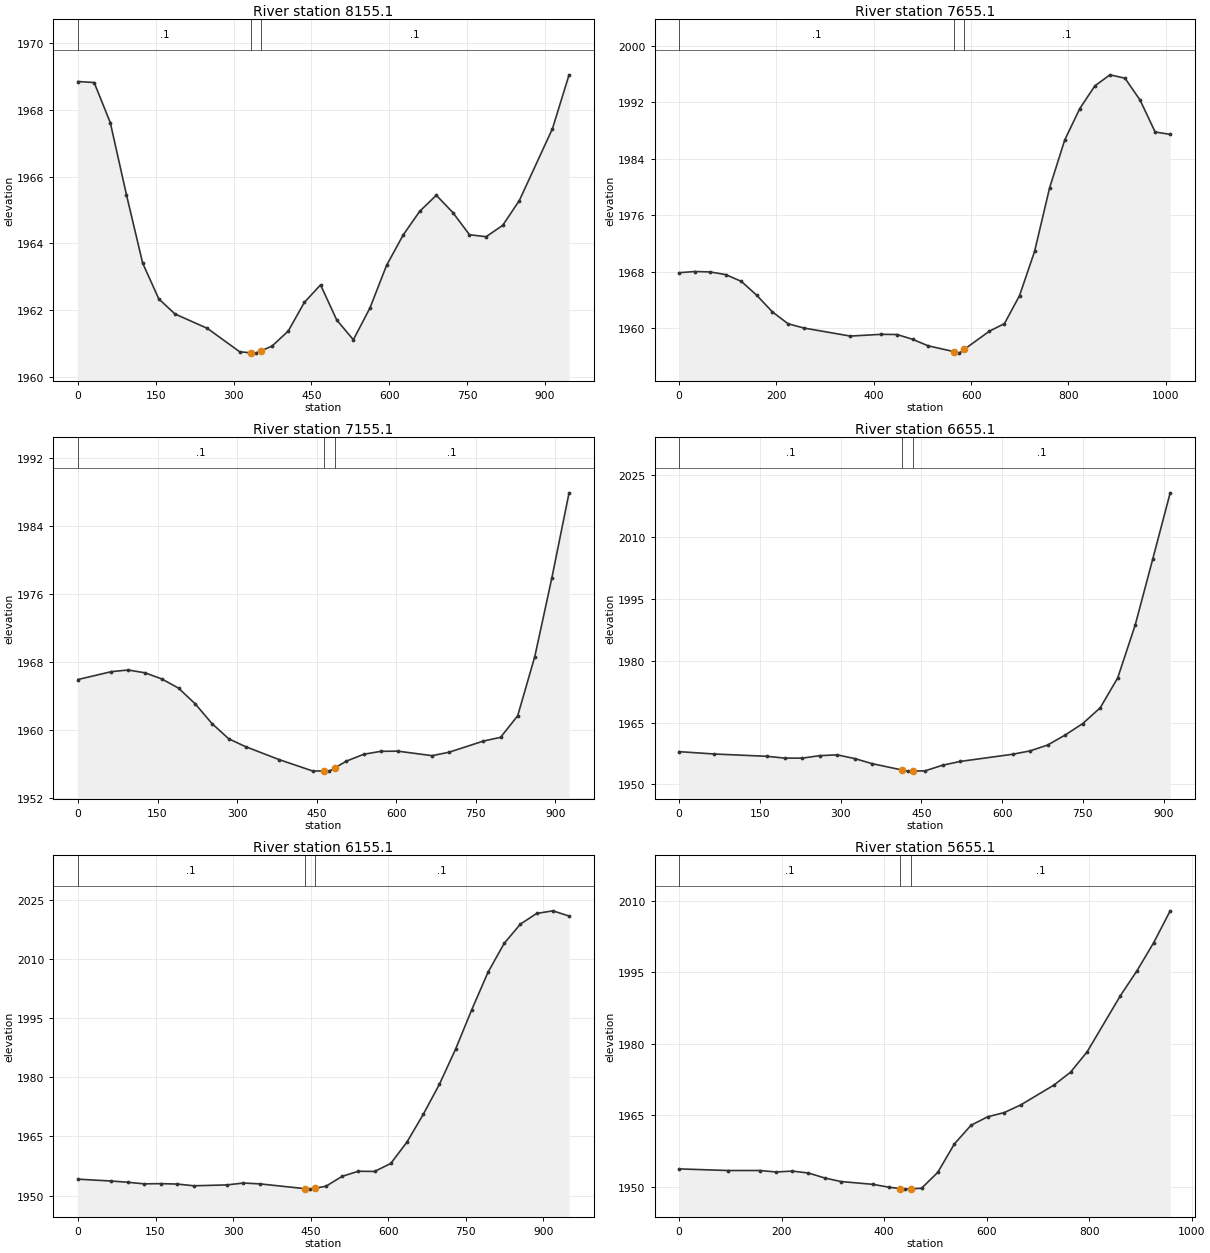
Type RM Length L Ch R = 1 ,8155.1,483.1,500,515.8
XS GIS Cut Line= 3
     2298617.080      734845.825     2298137.561      734708.799
     2297702.560      734603.000
#Sta/Elev= 30
       0 1968.84    31.2 1968.81    62.3 1967.61    93.5 1965.45   124.7 1963.41
   155.8 1962.34   187.0 1961.89   249.4 1961.46   311.7 1960.76   332.9 1960.73
   342.9 1960.72   352.9 1960.79   374.0 1960.93   405.2 1961.38   436.4 1962.24
   467.5 1962.76   498.7 1961.71   530.7 1961.12   562.7 1962.07   594.6 1963.34
   626.6 1964.25   658.6 1964.96   690.6 1965.44   722.6 1964.92   754.5 1964.26
   786.5 1964.20   818.5 1964.54   850.5 1965.28   914.4 1967.43   946.4 1969.04
#Mann= 3 , 0 , 0
       0     0.1       0   332.9   0.045       0   352.9     0.1       0
Bank Sta=332.9,352.9
Exp/Cntr=0.3,0.1

Type RM Length L Ch R = 1 ,7655.1,484.2,500,522.4
XS GIS Cut Line= 3
     2298681.793      734728.923     2298334.994      734269.416
     2298081.644      733917.578
#Sta/Elev= 30
       0 1967.84    32.0 1968.01    64.0 1967.95    96.0 1967.57   127.9 1966.61
   159.9 1964.62   191.9 1962.27   223.9 1960.60   255.9 1960.00   351.8 1958.85
   415.8 1959.10   447.8 1959.07   479.7 1958.40   511.7 1957.47   565.7 1956.63
   575.7 1956.43   585.7 1956.95   637.6 1959.54   668.6 1960.62   699.6 1964.59
   730.5 1970.86   761.5 1979.91   792.5 1986.68   823.4 1991.13   854.4 1994.35
   885.4 1995.92   916.3 1995.44   947.3 1992.34   978.3 1987.81  1009.2 1987.47
#Mann= 3 , 0 , 0
       0     0.1       0   565.7   0.045       0   585.7     0.1       0
Bank Sta=565.7,585.7
Exp/Cntr=0.3,0.1

Type RM Length L Ch R = 1 ,7155.1,493.1,500,499.4
XS GIS Cut Line= 3
     2298813.495      734703.125     2298816.888      734229.108
     2298935.735      733793.054
#Sta/Elev= 27
       0 1965.89    63.2 1966.82    94.8 1967.01   126.4 1966.68   158.0 1965.96
   189.6 1964.88   221.2 1963.02   252.8 1960.70   284.4 1958.91   316.0 1957.99
   379.2 1956.47   442.4 1955.13     464 1955.12   474.0 1955.11     484 1955.48
   506.3 1956.29   538.6 1957.09   570.9 1957.44   603.2 1957.46   667.7 1956.93
   700.0 1957.34   764.6 1958.65   796.9 1959.09   829.1 1961.62   861.4 1968.59
   893.7 1977.89   926.0 1987.86
#Mann= 3 , 0 , 0
       0     0.1       0     464   0.045       0     484     0.1       0
Bank Sta=464,484
Exp/Cntr=0.3,0.1

Type RM Length L Ch R = 1 ,6655.1,507.7,500,494.7
XS GIS Cut Line= 3
     2299182.344      734799.571     2299283.526      734354.030
     2299406.521      733915.799
#Sta/Elev= 25
       0 1957.93    65.3 1957.36   163.2 1956.80   195.8 1956.37   228.4 1956.35
   261.1 1956.96   293.7 1957.15   326.4 1956.24   359.0 1955.00   414.3 1953.47
   424.2 1953.20   434.3 1953.22   456.9 1953.27   489.4 1954.64   521.9 1955.55
   619.4 1957.30   652.0 1958.12   684.5 1959.54   717.0 1961.97   749.5 1964.74
   782.0 1968.57   814.5 1975.83   847.0 1988.67   879.5 2004.65   912.0 2020.78
#Mann= 3 , 0 , 0
       0     0.1       0   414.3   0.045       0   434.3     0.1       0
Bank Sta=414.3,434.3
Exp/Cntr=0.3,0.1

Type RM Length L Ch R = 1 ,6155.1,485,500,502.9
XS GIS Cut Line= 3
     2299773.922      734973.286     2299729.978      734527.111
     2299749.814      734025.707
#Sta/Elev= 29
       0 1954.16    64.0 1953.69    96.1 1953.38   128.1 1952.97   160.1 1953.02
   192.1 1952.92   224.2 1952.48   288.2 1952.70   320.2 1953.18   352.3 1952.96
   438.3 1951.76   448.3 1951.63   458.3 1951.86   479.7 1952.36   511.1 1954.88
   542.4 1956.17   573.8 1956.12   605.1 1958.14   636.5 1963.58   667.9 1970.60
   699.2 1978.24   730.6 1987.19   762.0 1997.25   793.3 2006.71   824.7 2014.07
   856.0 2018.94   887.4 2021.64   918.8 2022.31   950.1 2020.99
#Mann= 3 , 0 , 0
       0     0.1       0   438.3   0.045       0   458.3     0.1       0
Bank Sta=438.3,458.3
Exp/Cntr=0.3,0.1

Type RM Length L Ch R = 1 ,5655.1,507.3,500,483.5
XS GIS Cut Line= 3
     2299949.097      734986.820     2300159.260      734528.068
     2300303.564      734098.177
#Sta/Elev= 27
       0 1953.73    94.6 1953.39   157.7 1953.39   189.2 1953.08   220.8 1953.27
   252.3 1952.86   283.8 1951.83   315.4 1951.08   378.4 1950.48   410.0 1949.87
   431.5 1949.60   441.5 1949.48   451.5 1949.54   473.1 1949.67   504.6 1953.00
   537.0 1958.96   569.4 1962.88   601.8 1964.67   634.2 1965.55   666.6 1967.17
   731.3 1971.33   763.7 1974.04   796.1 1978.32   860.9 1990.09   893.3 1995.34
   925.7 2001.19   958.1 2007.92
#Mann= 3 , 0 , 0
       0     0.1       0   431.5   0.045       0   451.5     0.1       0
Bank Sta=431.5,451.5
Exp/Cntr=0.3,0.1

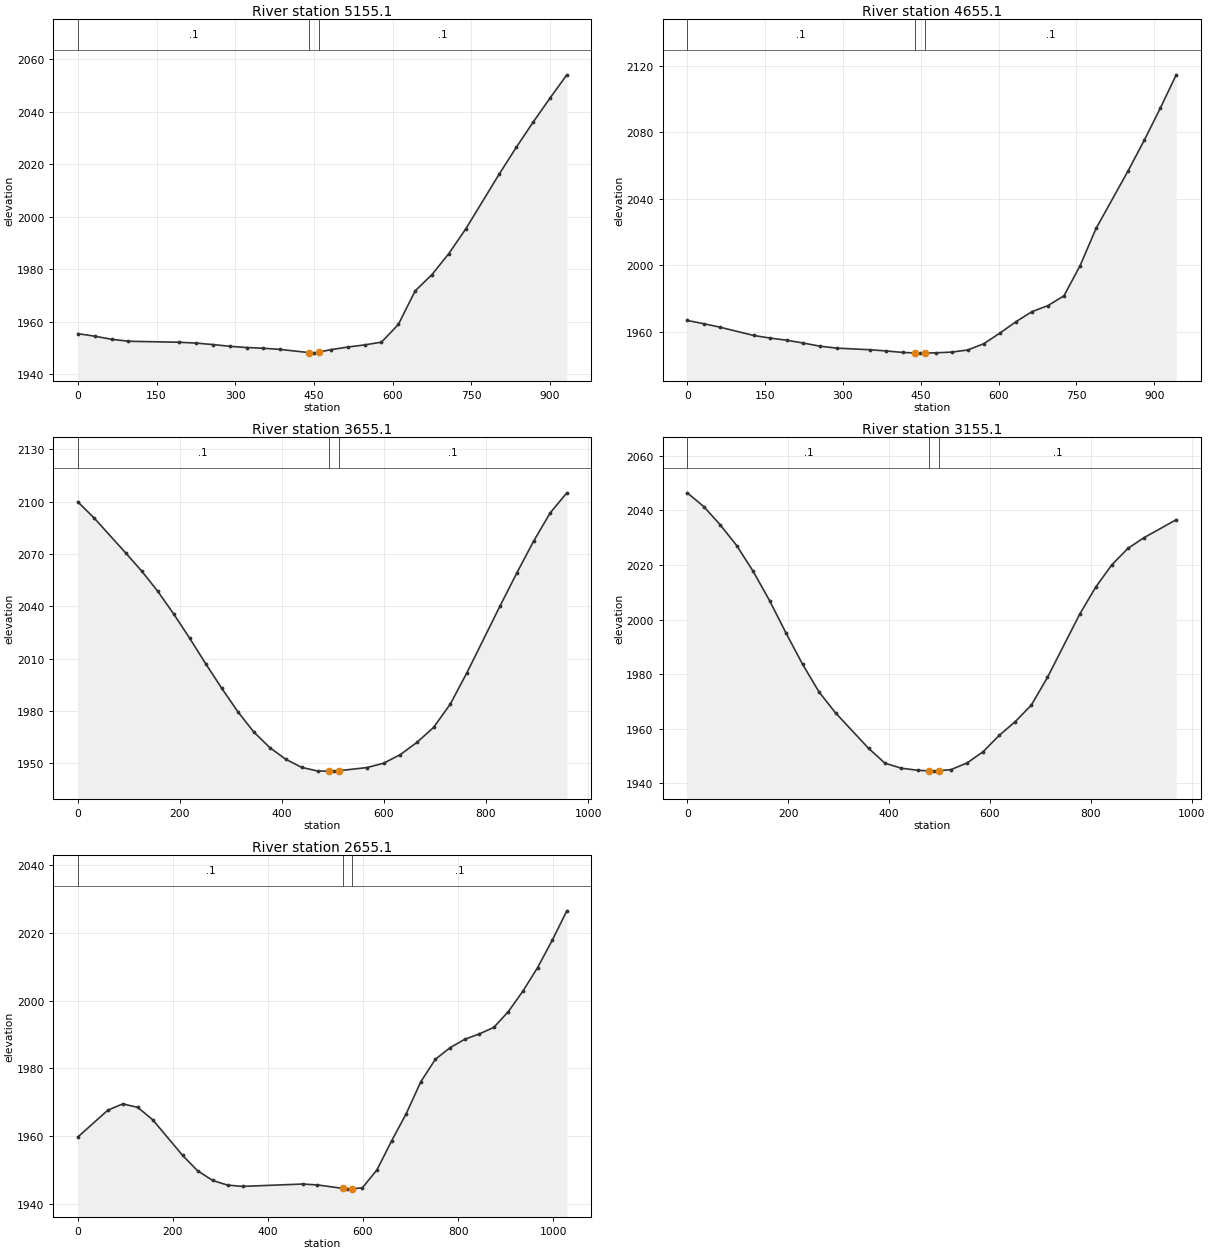
Type RM Length L Ch R = 1 ,5155.1,494.1,500,497.2
XS GIS Cut Line= 3
     2300505.840      735068.083     2300543.230      734619.371
     2300541.950      734137.553
#Sta/Elev= 28
       0 1955.42    32.2 1954.45    64.3 1953.28    96.5 1952.53   193.0 1952.15
   225.1 1951.83   257.3 1951.27   289.5 1950.61   321.6 1950.14   353.8 1949.86
   385.9 1949.41   440.3 1948.21   450.3 1948.00   460.3 1948.42   482.4 1949.34
   514.5 1950.31   546.6 1951.13   578.8 1952.19   610.9 1958.92   643.0 1971.73
   675.1 1977.97   707.2 1985.96   739.4 1995.34   803.6 2016.39   835.7 2026.43
   867.8 2036.04   900.0 2045.21   932.1 2054.09
#Mann= 3 , 0 , 0
       0     0.1       0   440.3   0.045       0   460.3     0.1       0
Bank Sta=440.3,460.3
Exp/Cntr=0.3,0.1

Type RM Length L Ch R = 1 ,4655.1,1024.5,1000,830.6
XS GIS Cut Line= 3
     2300868.704      735099.280     2300991.344      734668.336
     2300974.709      734174.260
#Sta/Elev= 30
       0 1966.83    32.0 1964.87    64.0 1962.71   128.0 1957.80   160.0 1956.22
   192.0 1954.94   224.0 1953.22   256.0 1951.34   288.0 1950.19   352.0 1949.22
   384.0 1948.48   416.0 1947.57   438.1 1947.30   448.0 1947.18   458.1 1947.24
   479.0 1947.37   509.8 1947.80   540.8 1949.08   571.6 1952.85   602.5 1959.20
   633.4 1966.04   664.3 1972.11   695.2 1975.77   726.1 1981.65   757.0 1999.69
   787.9 2022.14   849.7 2056.82   880.6 2075.06   911.5 2094.35   942.4 2114.53
#Mann= 3 , 0 , 0
       0     0.1       0   438.1   0.045       0   458.1     0.1       0
Bank Sta=438.1,458.1
Exp/Cntr=0.3,0.1

Type RM Length L Ch R = 1 ,3655.1,493.6,500,488.1
XS GIS Cut Line= 3
     2301783.297      734965.341     2301502.785      734549.817
     2301330.545      734126.539
#Sta/Elev= 30
       0 2099.82    31.3 2090.76    94.0 2070.47   125.3 2060.09   156.7 2048.54
   188.0 2035.50   219.3 2021.59   250.7 2007.00   282.0 1993.00   313.3 1979.66
   344.7 1967.98   376.0 1959.02   407.3 1952.33   438.7 1947.65   470.0 1945.56
   491.3 1945.53   501.4 1945.51   511.3 1945.75   566.6 1947.55   599.3 1950.05
   631.9 1954.97   664.6 1961.99   697.2 1970.58   729.8 1983.90   762.5 2001.91
   827.8 2040.40   860.4 2059.16   893.0 2077.18   925.7 2093.52   958.3 2105.00
#Mann= 3 , 0 , 0
       0     0.1       0   491.3   0.045       0   511.3     0.1       0
Bank Sta=491.3,511.3
Exp/Cntr=0.3,0.1

Type RM Length L Ch R = 1 ,3155.1,407,500,489.3
XS GIS Cut Line= 3
     2302074.761      734788.995     2301792.843      734348.819
     2301526.328      733990.359
#Sta/Elev= 30
       0 2046.40    32.7 2041.39    65.3 2034.70    98.0 2027.09   130.7 2017.65
   163.4 2006.87   196.0 1994.99   228.7 1983.60   261.4 1973.45   294.0 1965.81
   359.4 1952.85   392.0 1947.39   424.7 1945.54   457.4 1944.79     480 1944.58
   490.0 1944.48     500 1944.65   522.7 1945.03   554.6 1947.45   586.5 1951.59
   618.4 1957.56   650.3 1962.61   682.2 1968.67   714.2 1978.83   778.0 2001.94
   809.9 2011.90   841.8 2020.05   873.7 2026.06   905.6 2029.98   969.4 2036.55
#Mann= 3 , 0 , 0
       0     0.1       0     480   0.045       0     500     0.1       0
Bank Sta=480,500
Exp/Cntr=0.3,0.1

Type RM Length L Ch R = 1 ,2655.1,2762.3,2655.1,2641.3
XS GIS Cut Line= 3
     2302435.552      734518.012     2301969.505      734142.354
     2301594.556      733931.649
#Sta/Elev= 30
       0 1959.80    63.0 1967.69    94.5 1969.55   126.0 1968.52   157.5 1964.87
   220.5 1954.35   252.0 1949.83   283.6 1946.99   315.0 1945.61   346.6 1945.24
   472.6 1945.93   504.1 1945.67   557.1 1944.65   567.1 1944.43   577.1 1944.55
   598.6 1944.82   629.3 1950.12   660.0 1958.63   690.8 1966.66   721.5 1976.08
   752.2 1982.70   782.9 1986.09   813.6 1988.55   844.4 1990.16   875.1 1992.08
   905.8 1996.76   936.5 2002.82   967.2 2009.71   998.0 2017.76  1028.7 2026.43
#Mann= 3 , 0 , 0
       0     0.1       0   557.1   0.045       0   577.1     0.1       0
Bank Sta=557.1,577.1
Exp/Cntr=0.3,0.1