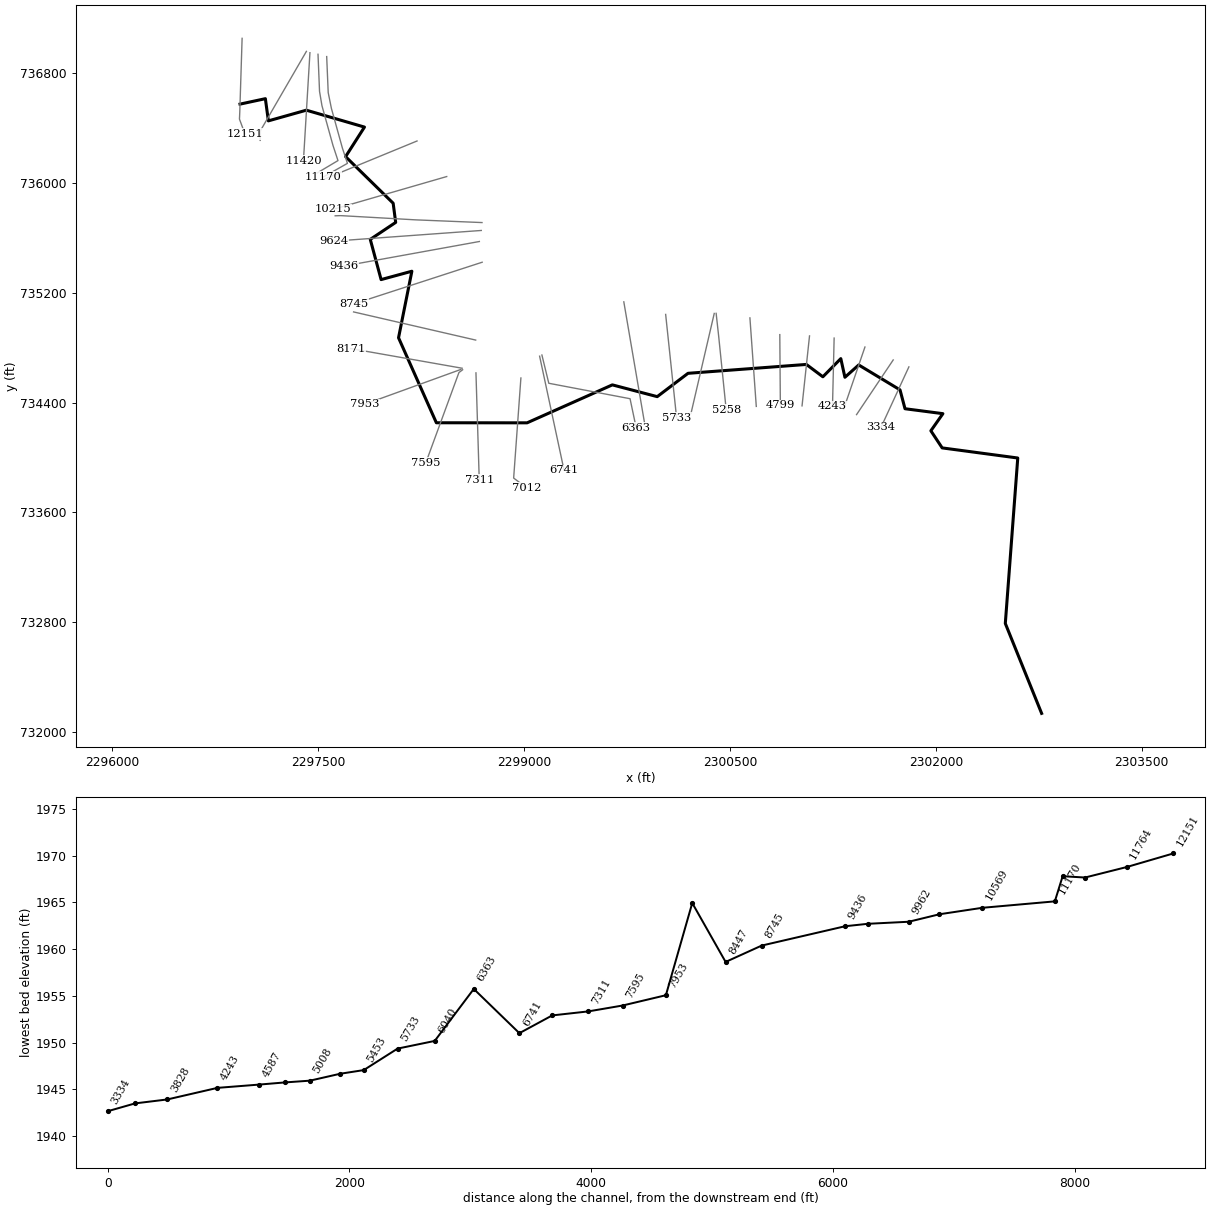
--- DAVISLCK.prj (project) ---

Proj Title=DAVISLCK
Current Plan=p01
Default Exp/Contr=0,0
English Units
Geom File=g01
Flow File=f01
Plan File=p01
BEGIN DESCRIPTION:
----------MODEL BY WOOD PLC 2022----------
AFH study
Randolph County, WV
HEC-RAS Version: RAS 6.2
Vertical Datum: NAVD88
Projection: NAD 1983 StatePlane West Virginia S FIPS 4702 (US Feet)
Terrain: 1-meter LIDAR (FEMA Region III 3DEP collected 2016-2018)
Land Use: 2019 NLCD
Hydrologic Method:
WV SIR2010-5033 regression equations
Additional Model Notes:
None
END DESCRIPTION:
DSS Export Rating Curves= 0
DSS Export Rating Curve Sorted= 0
DSS Export Volume Flow Curves= 0
DXF OffsetX= 0
DXF OffsetY= 0
DXF ScaleX= 0
DXF ScaleY= 0

--- DAVISLCK.p01 (plan) ---

Plan Title=Floodplain
Program Version=6.20
Short Identifier=Floodplain
Geom File=g01
Flow File=f01
Subcritical Flow
K Sum by GR= 0
Std Step Tol= 0.01
Critical Tol= 0.01
Num of Std Step Trials= 20
Max Error Tol= 0.3
Flow Tol Ratio= 0.001
Split Flow NTrial= 30
Split Flow Tol= 0.02
Split Flow Ratio= 0.02
Log Output Level= 0
Friction Slope Method= 1
Unsteady Friction Slope Method= 2
Unsteady Bridges Friction Slope Method= 1
Parabolic Critical Depth
Global Vel Dist= 0 , 0 , 0
Global Log Level= 0
CheckData=True
Encroach Param=-1 ,0,0, 0
Mapping Interval=1HOUR
Computation Time Step Use Courant=        0
Computation Time Step Use Time Series=    0
Computation Time Step Count To Double=0
Computation Time Step Max Doubling=0
Computation Time Step Max Halving=0
Computation Time Step Residence Courant=0
Run HTab= 0
Run UNet= 0
Run Sediment= 0
Run PostProcess= 0
Run WQNet= 0
Run RASMapper= 0
UNET Theta= 0
UNET Theta Warmup= 0
UNET ZTol= 0
UNET ZSATol= 0
UNET MxIter= 0
UNET Max Iter WO Improvement= 0
UNET MaxInSteps= 0
UNET DtIC= 0
UNET DtMin= 0
UNET MaxCRTS= 0
UNET WFStab= 0
UNET SFStab= 0
UNET WFX= 1
UNET SFX= 1
UNET Gravity=32.174
UNET 1D Methodology=Finite Difference
UNET DSS MLevel= 1
UNET Pardiso=0
UNET DZMax Abort= 0
UNET Use Existing IB Tables= 0
UNET Froude Reduction=False
UNET Froude Limit= 0
UNET Froude Power= 0
UNET D1 Cores= 0
UNET WindReference=Eulerian
UNET WindDragFormulation=Hsu (1988)
UNET D2 Coriolis=0
UNET D2 Cores= 0
UNET D2 Theta= 1
UNET D2 Theta Warmup= 1
UNET D2 Z Tol= 0.01
UNET D2 Volume Tol= 0.01
UNET D2 Max Iterations= 20
UNET D2 Equation= 0
UNET D2 RampUpFraction=0.1
UNET D2 TimeSlices= 1
UNET D2 Turbulence Formulation=Non-Conservative (original)
UNET D2 Eddy Viscosity=0.3
UNET D2 Transverse Eddy Viscosity=0.1
UNET D2 Smagorinsky Mixing=0
UNET D2 BCVolumeCheck=0
UNET D2 Cores=0
UNET D2 SolverType=PARDISO (Direct)
UNET D2 Minimum Iterations= 2147483647
UNET D2 Maximum Iterations= 2147483647
UNET D2 Restart Number= 10
UNET D2 Relaxation Coeff=1.3
UNET D2 SOR Precondition Iterations= 10
UNET D2 ILUT Maximum Fill= 8
UNET D2 ILUT Tolerance=1E-08
UNET D1D2 MaxIter= 0
UNET D1D2 ZTol=0.01
UNET D1D2 QTol=0.1
UNET D1D2 MinQTol=1
Write IC File= 0
Write IC File at Fixed DateTime=0
Write IC File at Sim End=0
Echo Input=False
Echo Parameters=False
Echo Output=False
Write Detailed= 0
HDF Write Warmup=0
HDF Write Time Slices=0
HDF Flush=0
HDF Compression= 1
HDF Chunk Size= 1
HDF Spatial Parts= 1
HDF Use Max Rows=0
HDF Fixed Rows= 1
Calibration Method= 0
Calibration Iterations= 20
Calibration Max Change=0.05
Calibration Tolerance=0.2
Calibration Maximum=1.5
Calibration Minimum=0.5
Calibration Optimization Method= 1
WQ AD Non Conservative
WQ ULTIMATE=-1
WQ Max Comp Step=1HOUR
WQ Output Interval=15MIN
WQ Output Selected Increments= 0
WQ Output face flow=0
WQ Output face velocity=0
WQ Output face area=0
WQ Output face dispersion=0
WQ Output cell volume=0
WQ Output cell surface area=0
WQ Output cell continuity=0
WQ Output cumulative cell continuity=0
WQ Output face conc=0
WQ Output face dconc_dx=0
WQ Output face courant=0
WQ Output face peclet=0
WQ Output face adv mass=0
WQ Output face disp mass=0
WQ Output cell mass=0
WQ Output cell source sink temp=0
WQ Output nsm pathways=0
WQ Output nsm derived pathways=0
WQ Create Restart=0
WQ Fixed Restart=0
WQ System Summary=0
WQ Write To DSS=0
Sorting and Armoring Iterations= 10
XS Update Threshold= 0.02
Bed Roughness Predictor= 0
Hydraulics Update Threshold= 0.02
Energy Slope Method= 1
Volume Change Method= 1
Sediment Retention Method= 0
Sediment TS Multiplier= 1
Warm Up Method= 0
XS Weighting Method= 0
Number of US Weighted Cross Sections= 1
Number of DS Weighted Cross Sections= 1
Upstream XS Weight=0
Main XS Weight=1
Downstream XS Weight=0
Number of DS XS's Weighted with US Boundary= 1
Upstream Boundary Weight= 1
Weight of XSs Associated with US Boundary= 0
Number of US XS's Weighted with DS Boundary= 1
Downstream Boundary Weight= 0.5
Weight of XSs Associated with DS Boundary= 0.5
Percentile Method= 0
Sediment Output Level= 3
Mass or Volume Output= 0
Output Increment Type= 1
Profile and TS Output Increment= 1
Transport Output Increment 1
XS Output Flag= 0
XS Output Increment= 10
Read HDF5 Sediment Hotstart= 0
Sediment Hotstart Type= 0
Write Gradation File= 0
Read Gradation Hotstart= 0
Write HDF5 File= 1
Write Binary Output= 1
Write DSS Sediment File= 0
DSS Sediment Output Type= 1
SV Curve= 0
Specific Gage Flag= 0
Subcell Erosion Methods= 0
Subcell Deposition Methods= 0
Advection Scheme= 1
Matrix Solver= 0
Implicit Weighting Factor= 1
Maximum Outer Loop Convergence Iterations= 5
Convergence Maximum Absolute= 0.001
Convergence RMSE= 0.0001
Grain Fractions Max Abs Error= 0.001
Max Subgrid Regions= 1
Max Subgrid Length Scale= 3.402823E+38
Initial Layer Thickness= 3.402823E+38
Min Layer Thickness= 3.402823E+38
Max Layer Thickness= 3.402823E+38
Number of Layers= 5

--- DAVISLCK.f01 (steady flow) ---

Flow Title=Flow
Program Version=6.20
Number of Profiles= 1
Profile Names=P100yr
River Rch & RM=DAVISLCK,Main,12151
     639
River Rch & RM=DAVISLCK,Main,5258
     746
Boundary for River Rch & Prof#=DAVISLCK,Main            , 1
Up Type= 0
Dn Type= 3
Dn Slope=0.00338
DSS Import GetInterval= 0
DSS Import GetPeak= 0
DSS Import FillOption= 0

--- DAVISLCK.g01 (geometry) ---

Geom Title=Geometry
Program Version=6.20

River Reach=DAVISLCK        ,Main
Reach XY= 30
2296932.46936871736575.5075022132297117.07200003736615.151999995
     2297138.932736453.4520000072297415.51000001736531.297000006
2297838.82900003736408.1280000062297701.27000001736192.790999994
2298047.78700003735853.2709999982298066.13800003735713.402999997
2297881.13500004735589.6310000122297959.99600002735296.641000003
2298184.04800002735357.6090000122298086.91900001734872.623999998
2298362.38500004734253.1720000212299023.12299998734252.726999998
2299644.07900001734529.362000018     2299970.954734443.573000014
2300195.19700004734613.5890000022301057.19500001734678.286000013
2301177.33300005734588.2300000192301308.07099999734720.739999995
2301337.97800004734584.6660000092301438.42700003734674.526000008
     2301739.308734492.9330000132301775.60900001734355.441000015
2302051.59300001 734319.554000022301963.92999999 734194.76700002
2302046.24700002734070.0230000172302596.82300001733996.344000012
2302506.13500004732790.6720000062302770.58600003732135.188000008

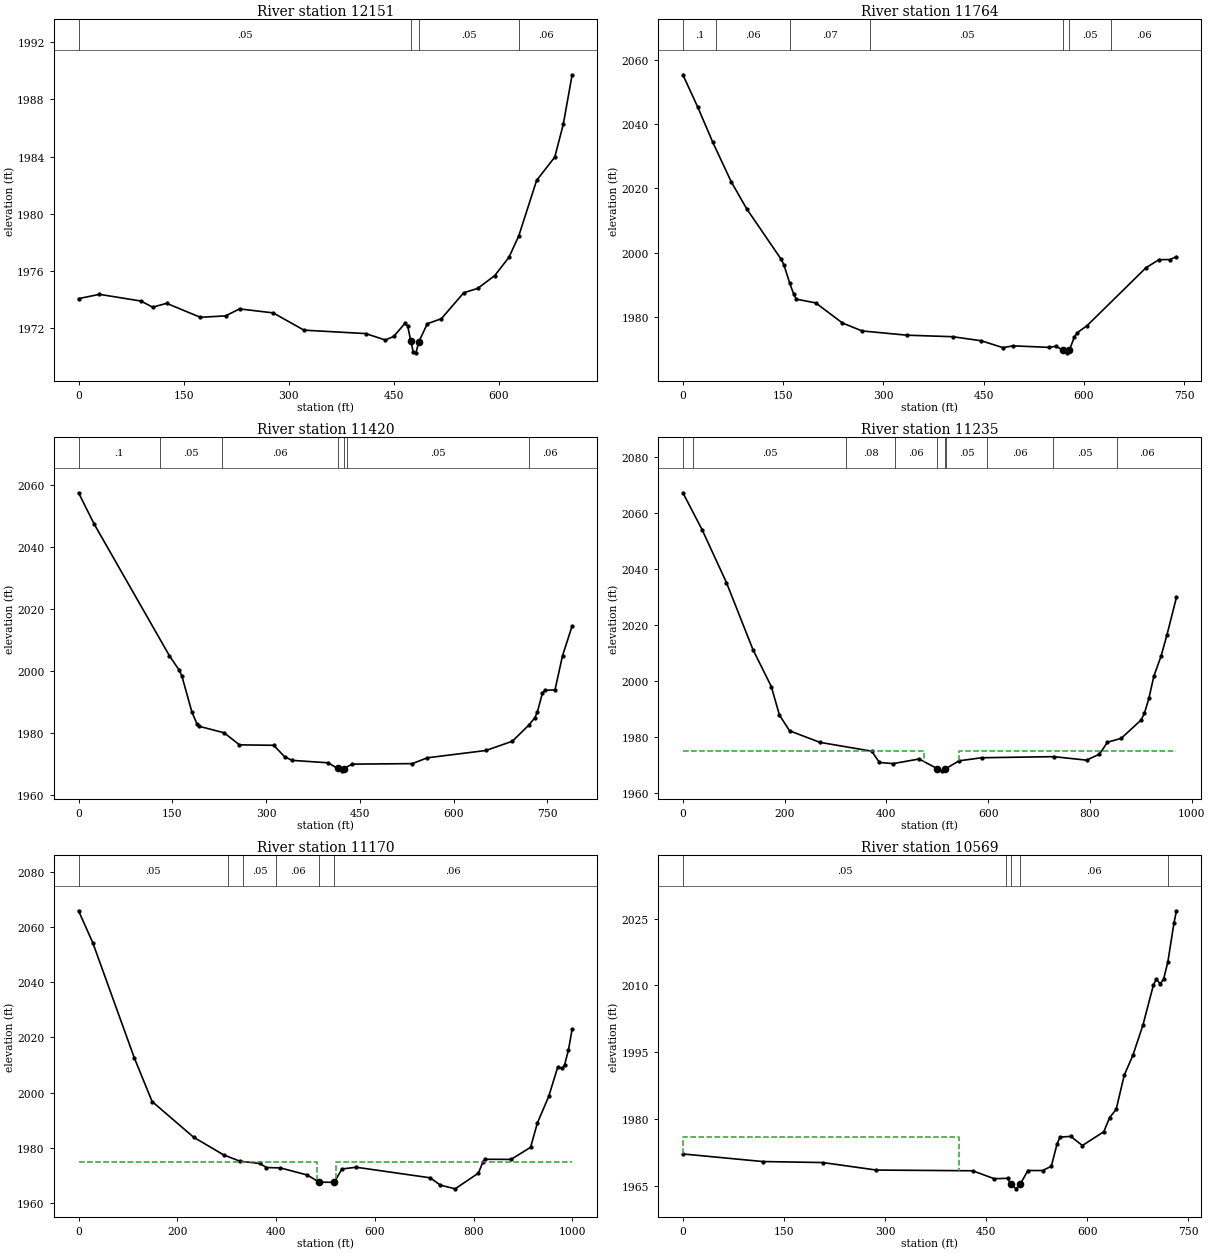
Type RM Length L Ch R = 1 ,12151   ,387.1,387.1,387.1
XS GIS Cut Line= 4
2296947.66111028737054.9472207442296930.58590594736516.066860767
2296928.37882519 736466.342915582296968.58002121736357.706788242
#Sta/Elev= 30
       0 1974.04    29.8 1974.34    89.2 1973.87   105.8 1973.44   125.8 1973.71
   173.9 1972.73   209.9 1972.83   229.9 1973.32   277.9 1973.04   321.9 1971.83
     410 1971.59     438 1971.14     450 1971.39     466  1972.3     470 1972.11
   474.5 1971.05     478 1970.28   481.8 1970.24  485.761971.001     498 1972.28
     518 1972.63     550 1974.45   570.1 1974.76   594.4 1975.66   614.6 1976.94
   628.6 1978.44   654.1 1982.33     680 1983.96   692.1 1986.25   704.8 1989.73
#Mann= 4 ,-1,0
       0     .05       0   474.5    .045       0  485.76     .05       0
  628.92     .06       0
Bank Sta=474.5,485.76
XS Rating Curve= 0 ,0
Exp/Cntr(USF)=0,0
Exp/Cntr=0.3,0.1

Type RM Length L Ch R = 1 ,11764   ,344.4,344.4,344.4
XS GIS Cut Line= 3
 2297415.8194231736959.8604921782297081.30905985736382.265427644
 2297079.1578678736311.276090104
#Sta/Elev= 30
       0 2055.32    22.2 2045.29    44.7 2034.33    72.4    2022    95.5 2013.59
   146.4 1998.11     151 1996.27   159.8  1990.5   165.6 1987.16   169.5  1985.5
   198.8 1984.31   238.8 1978.06   268.1  1975.6   335.4 1974.27   403.7  1973.8
   446.6 1972.53   478.8  1970.4   494.1 1970.95   548.5 1970.48     558 1970.84
   568.5 1969.63     574 1968.78   578.4 1969.68   585.5 1973.61   589.9 1975.03
   604.7 1977.24   692.9 1995.27   712.3 1997.78   728.6 1997.81   738.5 1998.73
#Mann= 7 ,-1,0
       0      .1       0      50     .06       0     160     .07       0
     280     .05       0   568.5    .045       0   578.4     .05       0
     640     .06       0
Bank Sta=568.5,578.4
XS Rating Curve= 0 ,0
Exp/Cntr(USF)=0,0
Exp/Cntr=0.3,0.1

Type RM Length L Ch R = 1 ,11420   ,185.1,185.1,185.1
BEGIN DESCRIPTION:
Structure XS 4
END DESCRIPTION:
XS GIS Cut Line= 2
2297441.63372766736950.1801279682297394.30750264 736161.76824286
#Sta/Elev= 30
       0 2057.57      25 2047.46   145.3 2004.92   161.3 2000.13   165.3 1998.36
   181.3 1986.71   189.3 1982.93   193.3 1982.04   232.9 1979.97   257.5 1976.06
   312.3 1975.92   329.6 1972.24   341.6 1971.05   399.3 1970.26  414.421968.456
   421.6 1967.66   424.21968.359   437.8 1969.83     534 1969.99     558 1971.87
   651.8 1974.24   694.1 1977.23     720 1982.34   730.3 1984.87   734.3 1986.83
   742.3 1992.81   746.3 1993.68   762.4 1993.86   774.4  2004.9   789.8  2014.5
#Mann= 7 ,-1,0
       0      .1       0     130     .05       0     230     .06       0
  414.42    .045       0   424.2     .06       0     430     .05       0
     720     .06       0
Bank Sta=414.42,424.2
XS Rating Curve= 0 ,0
Exp/Cntr(USF)=0,0
Exp/Cntr=0.5,0.3

Type RM Length L Ch R = 1 ,11235   ,64.6,64.6,64.6
BEGIN DESCRIPTION:
Structure XS 3 26.1ft
END DESCRIPTION:
XS GIS Cut Line= 6
2297500.46015063736938.7924128792297511.56847784736668.220371925
2297529.17166118736564.1168789252297609.31903883736274.926391019
2297645.90050651736163.9563749542297493.96812612736073.480138547
#Sta/Elev= 30
       0 2067.18    37.6 2054.05    85.7 2035.07   137.7 2011.14   173.8 1997.94
   189.8 1987.71   209.8  1982.1   269.2 1977.99   371.2 1974.82   386.3  1970.8
     413 1970.38   464.4 1972.03   500.4 1968.54   500.4 1968.53   508.7  1967.8
   515.8 1968.49   542.9 1971.38   587.3 1972.48   728.9 1972.87   793.4 1971.62
   818.7 1973.75   834.6 1978.03   861.4  1979.4   900.4 1985.92   907.1 1988.31
   916.1 1993.81   925.7 2001.64   939.7 2008.69   951.5 2016.41   970.2 2029.85
#Mann= 10 ,-1,0
       0      .1       0      20     .05       0   320.8     .08       0
  416.38     .06       0   500.4    .045       0   515.8     .06       0
  517.83     .05       0  597.83     .06       0  726.54     .05       0
  853.38     .06       0
#XS Ineff= 2 , 0
           474.3 1974.78   541.9         1974.78
Permanent Ineff=
       F       F
Bank Sta=500.4,515.8
XS Rating Curve= 0 ,0
Exp/Cntr(USF)=0,0
Exp/Cntr=0.5,0.3

Type RM Length L Ch R = 1 ,11170   ,601,601,601
BEGIN DESCRIPTION:
Structure XS 2 13.1ft 4.37
END DESCRIPTION:
XS GIS Cut Line= 6
2297563.62903992736922.0802154612297574.73736714736659.503498477
2297598.05149617736543.9781140922297678.19887382736254.787626185
 2297714.7803415 736143.81761012 2297538.8619892736044.203860605
#Sta/Elev= 30
       0 2065.91    28.9 2054.31     113 2012.57     149 1996.77   233.1 1983.82
   293.7 1977.44   327.1 1975.11   367.2 1974.31   380.7 1972.83   408.8  1972.7
   463.2 1970.13   487.5 1967.52  518.021967.474   533.5 1972.31   562.5 1972.94
   712.2 1969.11   733.1 1966.44   762.8 1965.11   809.9  1970.8     819 1974.83
   823.6 1975.83   876.1 1975.78   915.6 1980.16   929.4 1988.98   952.4 1998.64
   970.7  2009.3   979.9 2008.77   984.5 2010.09   992.3  2015.4   999.8    2023
#Mann= 6 ,-1,0
       0     .05       0  302.81     .08       0  332.81     .05       0
  400.67     .06       0   487.5    .045       0  518.02     .06       0
#XS Ineff= 2 , 0
          483.13 1974.78  522.39         1974.78
Permanent Ineff=
       F       F
Bank Sta=487.5,518.02
XS Rating Curve= 0 ,0
Exp/Cntr(USF)=0,0
Exp/Cntr=0.5,0.3

Type RM Length L Ch R = 1 ,10569   ,354,354,354
BEGIN DESCRIPTION:
Structure XS 1
END DESCRIPTION:
XS GIS Cut Line= 2
2298221.54738595736306.7592571292297544.48419796736028.064966674
#Sta/Elev= 30
       0 1972.24   118.3 1970.54   207.6 1970.31     287 1968.63   429.7 1968.47
   461.9 1966.69   481.6 1966.78   486.4 1965.43   494.6 1964.42  500.121965.416
   511.9 1968.53   533.5 1968.52   546.5 1969.47   555.2 1974.56   559.5 1976.02
   575.3 1976.18   592.6 1974.13   624.4 1977.22     633 1980.39   642.7 1982.22
   654.7 1989.89   667.6 1994.39   682.5 2001.16     698 2010.11   702.2  2011.4
   708.2 2010.35   713.2  2011.5   719.3  2015.2   728.5 2024.03   732.2 2026.74
#Mann= 5 ,-1,0
       0     .05       0     480     .06       0   486.4    .045       0
  500.12     .06       0     720      .1       0
#XS Ineff= 2 , 0
          409.27 1976.12
Permanent Ineff=
       F       F
Bank Sta=486.4,500.12
XS Rating Curve= 0 ,0
Exp/Cntr(USF)=0,0
Exp/Cntr=0.3,0.1

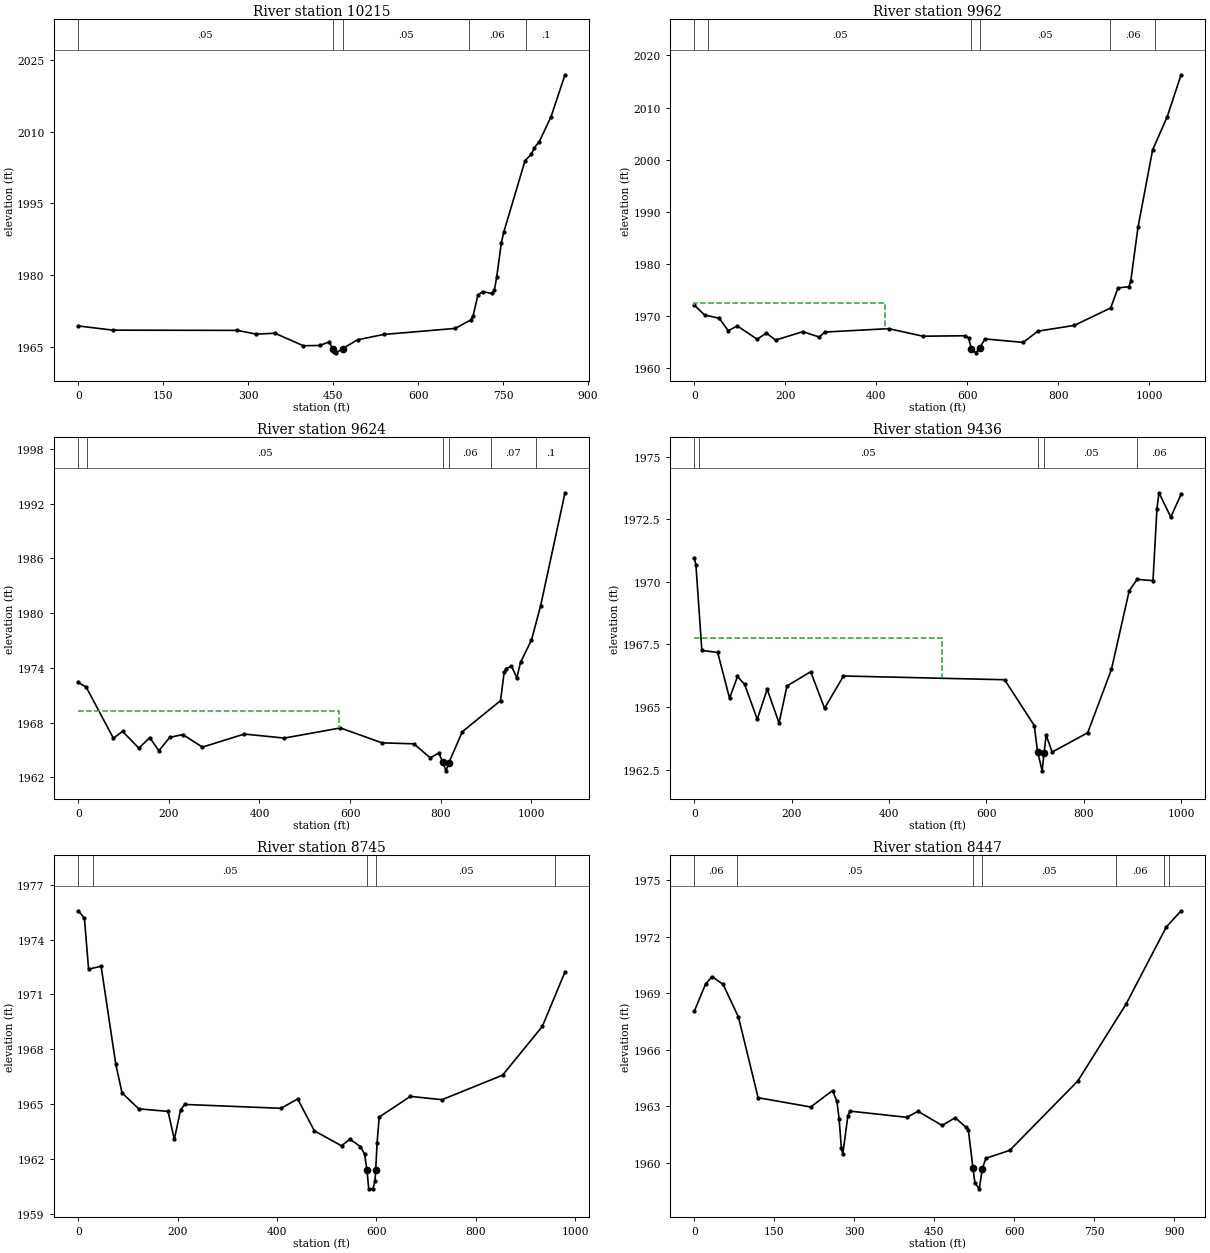
Type RM Length L Ch R = 1 ,10215   ,253.4,253.4,253.4
XS GIS Cut Line= 2
2298437.86104302736047.6204190922297612.35445458735808.716166304
#Sta/Elev= 30
       0 1969.36    61.5 1968.48   281.1 1968.43   314.1 1967.65   347.4 1967.83
   397.3 1965.22   426.1 1965.27   443.2 1966.01     449 1964.63   451.5  1963.9
   455.6 1963.73  466.82 1964.62   493.1 1966.46   539.4 1967.58   665.4 1968.84
     693 1970.61   697.2 1971.47   705.5 1975.76   713.8 1976.56   730.5 1976.16
   734.6  1976.8   738.8 1979.57   747.1 1986.77   751.3 1989.01   788.8 2003.94
   800.2 2005.36   805.4 2006.72   813.8 2007.91   834.6 2013.11   859.4 2021.95
#Mann= 5 ,-1,0
       0     .05       0     449    .045       0  466.82     .05       0
     690     .06       0     790      .1       0
Bank Sta=449,466.82
XS Rating Curve= 0 ,0
Exp/Cntr(USF)=0,0
Exp/Cntr=0.3,0.1

Type RM Length L Ch R = 1 ,9962    ,338.1,338.1,338.1
XS GIS Cut Line= 4
2298694.81022454735712.2540804932298211.20759283735732.037836332
2297663.99486722735762.9775151052297625.63341783735761.502074744
#Sta/Elev= 30
       0 1972.08    22.7 1970.19    54.7 1969.57    74.7 1967.18    94.7 1968.09
     138 1965.56   158.8  1966.7   178.8 1965.38   238.8 1966.99   274.9 1965.96
   286.9 1966.92   427.5 1967.57   503.1 1966.12   596.4 1966.21   603.2 1965.78
609.34521963.695   619.3 1962.93627.24521963.853   639.3  1965.6   723.4 1964.93
   755.5 1967.09   835.6 1968.19   915.7 1971.54   931.8 1975.38   955.8 1975.62
   959.8 1976.67   975.8 1987.03  1007.9 2001.87  1039.9 2008.19  1070.5 2016.28
#Mann= 6 ,-1,0
       0     .06       0      30     .05       0609.3452    .045       0
627.2452     .05       0  914.01     .06       0 1014.01      .1       0
#XS Ineff= 2 , 0
           419.9 1972.58
Permanent Ineff=
       F       F
Bank Sta=609.3452,627.2452
XS Rating Curve= 0 ,0
Exp/Cntr(USF)=0,0
Exp/Cntr=0.3,0.1

Type RM Length L Ch R = 1 ,9624    ,188.1,188.1,188.1
XS GIS Cut Line= 2
2298689.68370647735654.7107783882297618.25621603 735577.07202959
#Sta/Elev= 30
       0  1972.4    17.6 1971.89    77.7 1966.28    97.8 1967.04   133.9 1965.19
   157.9 1966.36     178 1964.91     202 1966.38     231 1966.68   274.2 1965.31
   366.5 1966.74   454.7  1966.3   578.7 1967.41   670.2 1965.78   740.7 1965.67
   776.9 1964.13   795.6 1964.66804.21251963.697   811.6 1962.71818.09251963.618
   847.7    1967   931.9  1970.4     940 1973.51     944 1973.89     956 1974.19
     968 1972.91   976.1  1974.6  1000.1 1977.03  1020.2 1980.75  1074.2 1993.18
#Mann= 6 ,-1,0
       0     .06       0      20     .05       0804.2125    .045       0
818.0925     .06       0     910     .07       0    1010      .1       0
#XS Ineff= 2 , 0
           576.6 1969.25
Permanent Ineff=
       F       F
Bank Sta=804.2125,818.0925
XS Rating Curve= 0 ,0
Exp/Cntr(USF)=0,0
Exp/Cntr=0.3,0.1

Type RM Length L Ch R = 1 ,9436    ,690.7,690.7,690.7
XS GIS Cut Line= 2
2298675.53922453735574.1971701962297691.42915443 735395.74583164
#Sta/Elev= 30
       0 1970.97     3.4 1970.67    15.6 1967.26    48.1 1967.18    72.5 1965.35
    88.8 1966.22   103.6  1965.9   129.4 1964.51   149.8 1965.71   174.2 1964.36
   190.4 1965.84   239.2 1966.41   267.7 1964.95   306.6 1966.24   637.6 1966.09
   698.6 1964.26705.24331963.216   714.8 1962.45718.80331963.182     723 1963.88
   735.2  1963.2   808.3 1963.97   857.1  1966.5   893.7 1969.65     910  1970.1
   942.5 1970.05   950.6 1972.92   954.7 1973.56   979.1 1972.59  1000.2  1973.5
#Mann= 5 ,-1,0
       0     .07       0      10     .05       0705.2433    .045       0
718.8033     .05       0     910     .06       0
#XS Ineff= 2 , 0
          509.44 1967.75
Permanent Ineff=
       F       F
Bank Sta=705.2433,718.8033
XS Rating Curve= 0 ,0
Exp/Cntr(USF)=0,0
Exp/Cntr=0.3,0.1

Type RM Length L Ch R = 1 ,8745    ,298.3,298.3,298.3
XS GIS Cut Line= 2
2298696.06142839735423.1902745742297764.72968293735120.541934882
#Sta/Elev= 30
       0 1975.57    12.5 1975.17    20.9 1972.38    46.1 1972.54    75.6 1967.19
    88.2 1965.62   121.9 1964.75   180.7 1964.61   193.4 1963.08     206  1964.7
   214.4 1964.99   407.9 1964.78   441.5 1965.29   475.1 1963.55   529.8 1962.73
   546.6 1963.09   567.7 1962.69   576.1 1962.28  580.91  1961.4   584.5 1960.38
   592.9 1960.38   597.1 1960.81  598.51 1961.41   601.3  1962.9   605.5  1964.3
   668.1 1965.43   731.9 1965.25   853.7 1966.59   933.6 1969.25   979.3 1972.23
#Mann= 5 ,-1,0
       0     .06       0      30     .05       0  580.91    .045       0
  598.51     .05       0     960     .06       0
Bank Sta=580.91,598.51
XS Rating Curve= 0 ,0
Exp/Cntr(USF)=0,0
Exp/Cntr=0.3,0.1

Type RM Length L Ch R = 1 ,8447    ,276,276,276
XS GIS Cut Line= 2
2298648.83681108734855.8102448412297759.62265333 735060.96974579
#Sta/Elev= 30
       0 1968.04    21.2 1969.49    33.5 1969.88      54 1969.47    82.8 1967.74
   119.7 1963.46   218.2 1962.97   259.3 1963.84   267.5 1963.26   271.6 1962.32
   275.7 1960.81   278.5 1960.48     288 1962.51   291.9 1962.75   398.6 1962.42
   419.4 1962.74   464.6 1961.99   489.2  1962.4   508.7 1961.91   513.8 1961.75
  522.55 1959.72   526.1 1958.94   534.3 1958.63   539.9 1959.69   546.7 1960.25
   591.4 1960.67   719.1 1964.35   809.4 1968.42   884.9 1972.51   912.6 1973.37
#Mann= 7 ,-1,0
       0     .06       0      80     .05       0  522.55    .045       0
   539.9     .05       0     790     .06       0     880     .05       0
     890     .06       0
Bank Sta=522.55,539.9
XS Rating Curve= 0 ,0
Exp/Cntr(USF)=0,0
Exp/Cntr=0.3,0.1

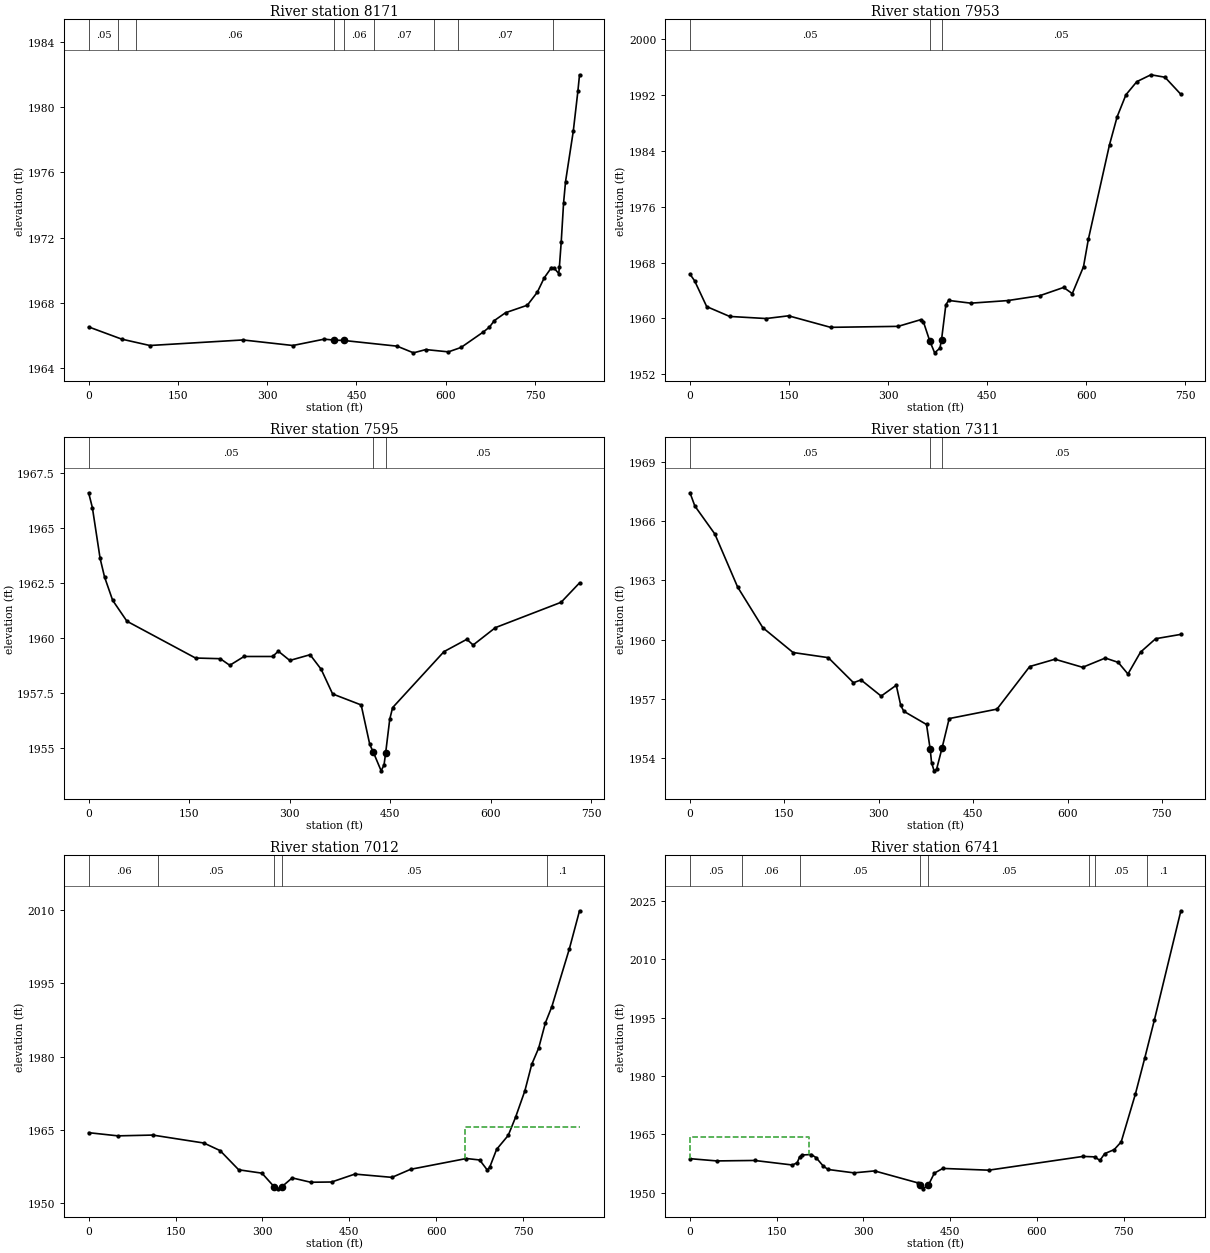
Type RM Length L Ch R = 1 ,8171    ,218.1,218.1,218.1
BEGIN DESCRIPTION:
Structure
END DESCRIPTION:
XS GIS Cut Line= 2
2298550.04563253734650.6477645922297737.79955324734794.059998107
#Sta/Elev= 30
       0 1966.52    55.6 1965.77   102.8 1965.38   259.3 1965.72   343.1 1965.38
   395.9 1965.77   412.1 1965.71   428.3 1965.69   518.2 1965.34   545.8 1964.93
   566.5 1965.13   604.5 1964.99   625.7 1965.26   663.2 1966.21   673.5 1966.51
   681.7 1966.91   700.5 1967.39   737.1 1967.85   753.9 1968.65   765.5 1969.53
   777.7 1970.16   781.8 1970.14   789.9 1969.79   790.9 1970.17     794 1971.71
     798 1974.12   801.3 1975.43   814.3 1978.52     822 1980.96   824.8 1981.98
#Mann= 9 ,-1,0
       0     .05       0      50     .07       0      80     .06       0
   412.1    .045       0   428.3     .06       0     480     .07       0
     580     .06       0     620     .07       0     780     .06       0
Bank Sta=412.1,428.3
XS Rating Curve= 0 ,0
Exp/Cntr(USF)=0,0
Exp/Cntr=0.3,0.1

Type RM Length L Ch R = 1 ,7953    ,357.7,357.7,357.7
XS GIS Cut Line= 2
2298540.54829802734641.7862152762297841.44331074734388.309803405
#Sta/Elev= 30
       0 1966.33       7 1965.38    25.3 1961.69    60.1 1960.28   115.3 1959.98
   149.3 1960.37     213 1958.72   315.3 1958.86   349.3 1959.81   353.5 1959.54
     363 1956.83   370.6 1955.07   378.6 1955.74  381.081956.964   387.6 1961.95
   391.8 1962.57   425.4 1962.18   481.2 1962.55   529.9 1963.25     566 1964.43
   579.1 1963.55   596.1  1967.4   603.4  1971.3   635.5 1984.86   647.1 1988.87
   660.4 1992.01   676.9 1993.89   698.2 1994.87   719.5 1994.52   743.6 1992.07
#Mann= 3 ,-1,0
       0     .05       0     363    .045       0  381.08     .05       0
Bank Sta=363,381.08
XS Rating Curve= 0 ,0
Exp/Cntr(USF)=0,0
Exp/Cntr=0.3,0.1

Type RM Length L Ch R = 1 ,7595    ,283.7,283.7,283.7
XS GIS Cut Line= 3
2298553.70675258  734639.49194872298526.78433534734619.101855609
2298286.28857965733963.382979369
#Sta/Elev= 30
       0 1966.59     5.6 1965.91    17.1 1963.61    23.7 1962.77    35.8 1961.71
    57.1 1960.76   159.4 1959.09   196.3 1959.06   210.5 1958.76   231.8 1959.16
   274.4 1959.16   282.9  1959.4     300 1958.98   330.3 1959.24   346.8 1958.58
   363.9 1957.46   406.5 1956.96   419.3 1955.17   424.7 1954.81   436.3 1953.97
   440.6 1954.24     443 1954.78   449.1 1956.31   453.4 1956.84     530 1959.38
   564.1 1959.94   573.5 1959.68   606.7 1960.47   704.7 1961.62   732.2  1962.5
#Mann= 3 ,-1,0
       0     .05       0   424.7    .045       0     443     .05       0
Bank Sta=424.7,443
XS Rating Curve= 0 ,0
Exp/Cntr(USF)=0,0
Exp/Cntr=0.3,0.1

Type RM Length L Ch R = 1 ,7311    ,299,299,299
XS GIS Cut Line= 2
2298650.76599372734616.8574568272298674.76422105733837.118036423
#Sta/Elev= 30
       0 1967.44     7.7 1966.77    39.5 1965.35    75.7 1962.66   115.7  1960.6
   163.8 1959.34   219.8 1959.08   259.8 1957.81   271.8 1957.95   303.8 1957.13
   327.8 1957.68   334.9 1956.66   339.8 1956.36   375.9 1955.69381.69991954.438
   383.9 1953.76   387.9 1953.34   391.9 1953.42400.59991954.503   411.9 1955.99
   487.9 1956.47   539.9 1958.63     580    1959     624 1958.59     660 1959.06
   680.5 1958.84     696 1958.25     716 1959.36     740 1960.04   780.1 1960.26
#Mann= 3 ,-1,0
       0     .05       0381.6999    .045       0400.5999     .05       0
Bank Sta=381.6999,400.5999
XS Rating Curve= 0 ,0
Exp/Cntr(USF)=0,0
Exp/Cntr=0.3,0.1

Type RM Length L Ch R = 1 ,7012    ,271.6,271.6,271.6
XS GIS Cut Line= 3
2298978.12256504 734579.526874222298925.35911394733850.140908137
2299018.07424685733780.431432804
#Sta/Elev= 30
       0 1964.41    50.5 1963.76   110.6 1963.92   198.9 1962.29   226.9 1960.74
     259 1956.81   299.1 1956.12   320.3 1953.32   327.2 1952.91   333.1  1953.3
   351.3 1955.15   383.3 1954.26   419.4 1954.31   459.5 1955.93   523.5 1955.26
   555.8 1956.91     652 1959.12   674.9 1958.82   688.1 1956.76   692.2 1957.31
   704.2    1961   724.2 1963.85   736.8 1967.54   752.9 1972.96   764.8  1978.4
   776.8 1981.74   788.3 1986.88   799.5 1990.21   829.9 2002.12   847.3 2009.85
#Mann= 5 ,-1,0
       0     .06       0     120     .05       0   320.3    .045       0
   333.1     .05       0  791.29      .1       0
#XS Ineff= 2 , 0
                          648.95         1965.66
Permanent Ineff=
       F       F
Bank Sta=320.3,333.1
XS Rating Curve= 0 ,0
Exp/Cntr(USF)=0,0
Exp/Cntr=0.3,0.1

Type RM Length L Ch R = 1 ,6741    ,377.3,377.3,377.3
XS GIS Cut Line= 2
  2299114.412013734738.4429700432299292.16576079733908.296707558
#Sta/Elev= 30
       0 1958.77    46.3 1958.19   111.7 1958.31   177.2 1957.14   185.4 1957.73
   189.5 1959.18   193.6 1959.71   209.9 1959.84   218.2 1959.02   230.4 1956.88
   238.8 1955.99   283.5 1955.12   319.3 1955.62     394 1952.55   398.1 1951.88
   402.2 1951.01   412.1 1951.92   422.6 1955.04   437.2 1956.26   516.7 1955.81
   679.8 1959.35     700 1959.23     709 1958.31   717.2 1960.06   733.7  1961.1
   745.8 1963.09   770.3 1975.37   786.7 1984.74   803.1 1994.39     849 2022.53
#Mann= 8 ,-1,0
       0     .05       0      90     .06       0     190     .05       0
   398.1    .045       0   412.1     .05       0     690      .1       0
     700     .05       0     790      .1       0
#XS Ineff= 2 , 0
          206.33 1964.41
Permanent Ineff=
       F       F
Bank Sta=398.1,412.1
XS Rating Curve= 0 ,0
Exp/Cntr(USF)=0,0
Exp/Cntr=0.3,0.1

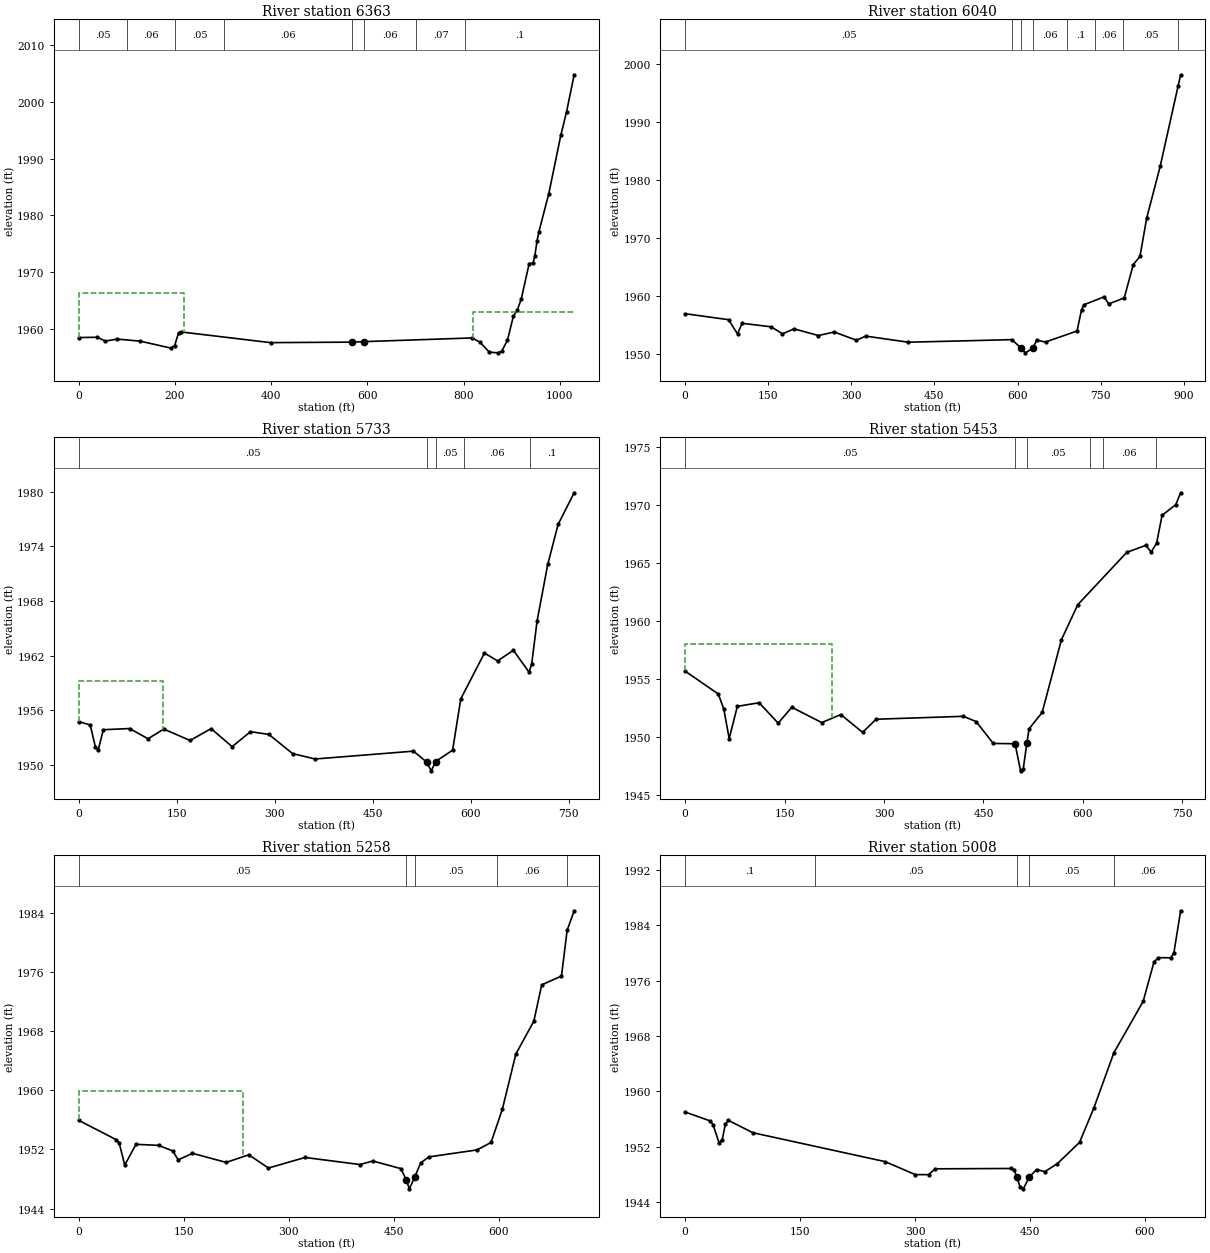
Type RM Length L Ch R = 1 ,6363    ,323.2,323.2,323.2
BEGIN DESCRIPTION:
Structure-- IFA added to raise WSE over bank stations
END DESCRIPTION:
XS GIS Cut Line= 4
2299131.13586479734746.9740634992299181.29070278734541.017880792
2299773.10684412734428.4815583222299817.45202386734217.608343139
#Sta/Elev= 30
       0 1958.44    38.9 1958.49    55.4 1957.81    80.1 1958.17   128.2  1957.8
   191.1 1956.59   199.5 1956.99   207.6 1959.26   211.8 1959.44     399 1957.54
567.7487 1957.63593.5486 1957.72   817.8 1958.37   834.1 1957.61   853.5 1955.87
   870.9 1955.74   879.1    1956   891.3 1957.98   903.6 1962.22   911.8 1963.29
     920 1965.28   936.3 1971.45   944.7  1971.6   948.1 1972.83   952.7 1975.48
   956.7 1977.15   977.2 1983.84  1002.1 1994.13    1014 1998.25  1029.9 2004.81
#Mann= 8 ,-1,0
       0     .05       0     100     .06       0     200     .05       0
  301.98     .06       0567.7487    .045       0593.5486     .06       0
  701.98     .07       0  801.98      .1       0
#XS Ineff= 2 , 0
          219.79 1966.38  820.12         1963.03
Permanent Ineff=
       F       F
Bank Sta=567.7487,593.5486
XS Rating Curve= 0 ,0
Exp/Cntr(USF)=0,0
Exp/Cntr=0.3,0.1

Type RM Length L Ch R = 1 ,6040    ,307.1,307.1,307.1
XS GIS Cut Line= 2
2299727.64355473735134.4635829092299878.43627346734252.864378243
#Sta/Elev= 30
       0 1956.92    78.4 1955.89    94.6 1953.43   102.8 1955.27   155.5 1954.66
   175.8 1953.45   196.7 1954.31   240.7 1953.16   269.1 1953.77   309.3 1952.35
     326 1953.06   403.1 1952.01   589.7 1952.45607.11881950.956   614.1 1950.18
627.88341950.979   634.4 1952.35   650.6 1952.05   707.4 1953.94   715.5 1957.58
   719.6 1958.45   756.1 1959.82   764.6 1958.61   792.6 1959.63   808.9 1965.38
     821 1966.78   833.1 1973.37   857.6 1982.35     890  1996.2   894.4 1998.06
#Mann= 8 ,-1,0
       0     .05       0     590     .06       0607.1188    .045       0
627.8834     .06       0     690      .1       0     740     .06       0
     790     .05       0     890      .1       0
Bank Sta=607.1188,627.8834
XS Rating Curve= 0 ,0
Exp/Cntr(USF)=0,0
Exp/Cntr=0.3,0.1

Type RM Length L Ch R = 1 ,5733    ,280.2,280.2,280.2
XS GIS Cut Line= 2
2300032.38088983735042.7674229542300112.14602668734288.717579021
#Sta/Elev= 30
       0 1954.77    17.7 1954.39    25.7 1951.98    29.8  1951.6    37.8 1953.87
      78    1954   106.2 1952.88   130.3 1953.94   170.5 1952.69   202.7 1953.99
   234.9 1952.01     263 1953.66   291.2 1953.35   327.4 1951.25   361.9 1950.66
   512.4 1951.52532.45021950.327   539.6 1949.36   546.3 1950.38   572.3 1951.63
   584.8 1957.26     621 1962.28   641.1 1961.42   665.3 1962.58   689.4 1960.17
   693.4 1961.13   701.5 1965.78   717.9 1972.01   733.7 1976.39   758.3 1979.86
#Mann= 5 ,-1,0
       0     .05       0532.4502    .045       0   546.3     .05       0
     590     .06       0     690      .1       0
#XS Ineff= 2 , 0
          128.89 1959.21
Permanent Ineff=
       F       F
Bank Sta=532.4502,546.3
XS Rating Curve= 0 ,0
Exp/Cntr(USF)=0,0
Exp/Cntr=0.3,0.1

Type RM Length L Ch R = 1 ,5453    ,194.6,194.6,194.6
XS GIS Cut Line= 2
2300386.23454627735049.9456164922300217.04983637734321.914987149
#Sta/Elev= 30
       0 1955.66    50.1 1953.68    58.3  1952.4    66.5 1949.84    78.8 1952.62
   111.7 1952.93   140.4 1951.17   160.9 1952.54   206.1 1951.22   234.9 1951.91
   267.7 1950.38   288.2 1951.51   419.7 1951.76   438.9 1951.31   464.8 1949.42
497.74591949.397   505.9 1947.06     510 1947.22 515.4461949.456   518.8 1950.68
   538.6  1952.1   567.5 1958.35   592.2 1961.38   666.1 1965.89   694.8  1966.5
     703 1965.92   711.2  1966.7   719.4 1969.09     740    1970   747.4 1971.03
#Mann= 6 ,-1,0
       0     .05       0497.7459    .045       0 515.446     .05       0
     610     .07       0     630     .06       0     710      .1       0
#XS Ineff= 2 , 0
          221.14 1958.03
Permanent Ineff=
       F       F
Bank Sta=497.7459,515.446
XS Rating Curve= 0 ,0
Exp/Cntr(USF)=0,0
Exp/Cntr=0.3,0.1

Type RM Length L Ch R = 1 ,5258    ,250.5,250.5,250.5
XS GIS Cut Line= 3
2300400.07426959735050.5536375862300418.45201086734884.651415303
2300473.33382711734347.145017326
#Sta/Elev= 30
       0 1955.95    53.7 1953.33    57.7 1952.94    65.8 1949.89    81.9  1952.7
   114.1 1952.56   134.2 1951.81   142.2  1950.6   162.4 1951.48   210.6 1950.25
   242.8 1951.28   270.9 1949.49   323.2 1950.92   401.5 1949.96   419.7 1950.44
   459.9 1949.41467.72851947.851     472 1946.67479.62821948.269   488.1 1950.19
   500.1    1951   568.5 1951.94   588.6 1952.95   604.7 1957.45     624 1964.94
   649.6 1969.37   660.9  1974.3   689.1 1975.49   697.1 1981.66   707.2 1984.33
#Mann= 5 ,-1,0
       0     .05       0467.7285    .045       0479.6282     .05       0
  596.92     .06       0  696.92      .1       0
#XS Ineff= 2 , 0
          234.71 1959.98
Permanent Ineff=
       F       F
Bank Sta=467.7285,479.6282
XS Rating Curve= 0 ,0
Exp/Cntr(USF)=0,0
Exp/Cntr=0.3,0.1

Type RM Length L Ch R = 1 ,5008    ,209,209,209
XS GIS Cut Line= 2
2300646.09425167735017.5075258132300692.43672076734372.375047503
#Sta/Elev= 30
       0 1957.02    32.4 1955.75    36.4 1955.22    44.4 1952.55    48.5 1953.05
    52.5 1955.25    56.5 1955.81    88.6 1954.03     261 1949.86   300.6 1947.98
   317.8 1947.98   326.5 1948.82   425.4 1948.87   429.4 1948.71433.11011947.587
   437.5 1946.13   441.5 1945.93449.41841947.652   458.7 1948.72   469.5 1948.41
   485.6 1949.54   514.8 1952.63   533.6 1957.62   559.7 1965.59   597.9    1973
   612.1 1978.72   617.9 1979.31     634 1979.29     638 1980.01   646.8 1986.08
#Mann= 5 ,-1,0
       0      .1       0     170     .05       0433.1101    .045       0
449.4184     .05       0     560     .06       0
Bank Sta=433.1101,449.4184
XS Rating Curve= 0 ,0
Exp/Cntr(USF)=0,0
Exp/Cntr=0.3,0.1

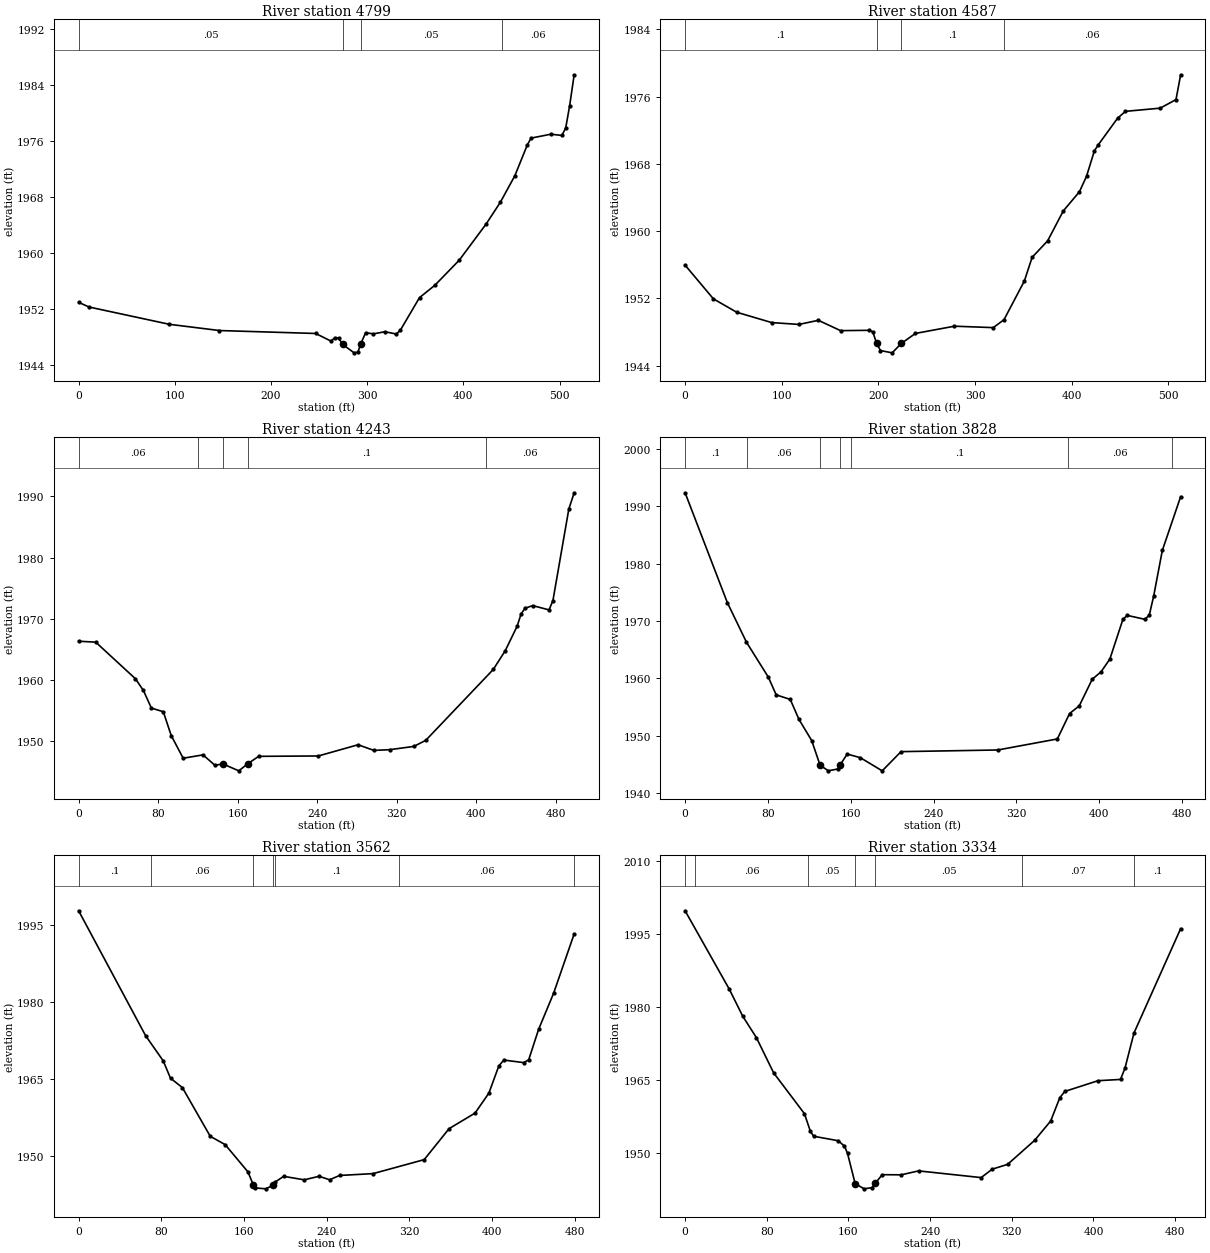
Type RM Length L Ch R = 1 ,4799    ,211.6,211.6,211.6
XS GIS Cut Line= 2
2300863.73534669734895.5661995972300867.71903567734380.342425454
#Sta/Elev= 30
       0 1952.97    10.7  1952.3    94.4 1949.82   146.4 1948.93   246.4 1948.51
   262.4 1947.42   266.4 1947.91   270.4 1947.85   274.4 1946.95   286.4 1945.74
   290.4 1945.86  293.321947.022   298.4 1948.63   306.4 1948.45   318.4 1948.76
   330.4 1948.43   334.4 1948.96   354.4 1953.64   370.4 1955.41   395.8 1959.01
   423.6 1964.16   438.4 1967.27   453.5 1971.07   466.4 1975.46   470.4 1976.46
     491 1977.02   502.4 1976.84   506.4 1977.91   510.4 1981.01   515.2 1985.52
#Mann= 4 ,-1,0
       0     .05       0   274.4    .045       0  293.32     .05       0
     440     .06       0
Bank Sta=274.4,293.32
XS Rating Curve= 0 ,0
Exp/Cntr(USF)=0,0
Exp/Cntr=0.3,0.1

Type RM Length L Ch R = 1 ,4587    ,344.2,344.2,344.2
XS GIS Cut Line= 2
2301080.18244769734886.2709253212301025.73869836734376.358736478
#Sta/Elev= 30
       0 1955.94    29.3 1951.93    53.4 1950.34    89.6 1949.11   117.8 1948.89
   137.9 1949.38   160.9 1948.15   190.2 1948.19   194.2 1948.02   198.2 1946.64
   202.2 1945.78   214.3 1945.51  223.751946.631   238.4 1947.82   278.7 1948.68
   318.9 1948.51     330 1949.45   351.1 1954.06   359.1 1956.87   375.2 1958.84
   391.3 1962.38   408.1 1964.68   415.4 1966.51   423.5 1969.53   427.5 1970.25
   447.6 1973.43   455.7 1974.24   491.7 1974.62     508 1975.64   512.8 1978.59
#Mann= 4 ,-1,0
       0      .1       0   198.2    .045       0  223.75      .1       0
     330     .06       0
Bank Sta=198.2,223.75
XS Rating Curve= 0 ,0
Exp/Cntr(USF)=0,0
Exp/Cntr=0.3,0.1

Type RM Length L Ch R = 1 ,4243    ,415.3,415.3,415.3
XS GIS Cut Line= 2
2301259.44845158 734870.336169422301247.49738465734371.784420468
#Sta/Elev= 30
       0 1966.34    17.2 1966.19    57.2  1960.2    65.2 1958.29    73.2 1955.42
    85.2 1954.82    93.2 1950.92   105.2 1947.22   125.2 1947.77   137.2 1946.06
     145  1946.3   161.2 1945.16     170  1946.3   181.2 1947.53   241.2 1947.59
   281.2 1949.42   297.2  1948.5   313.2 1948.62   337.3 1949.15   349.3 1950.14
   417.3 1961.73   429.3 1964.78   441.3  1968.8   445.3 1970.81   449.3 1971.74
     457 1972.16   473.4 1971.46   477.3 1972.97   493.3 1987.93   498.7  1990.6
#Mann= 5 ,-1,0
       0     .06       0     120      .1       0     145    .045       0
     170      .1       0     410     .06       0
Bank Sta=145,170
XS Rating Curve= 0 ,0
Exp/Cntr(USF)=0,0
Exp/Cntr=0.3,0.1

Type RM Length L Ch R = 1 ,3828    ,265.9,265.9,265.9
XS GIS Cut Line= 2
2301483.86293052734805.2692494892301328.49906048734352.456602626
#Sta/Elev= 30
       0 1992.31    40.8  1973.2    59.3  1966.3    80.4 1960.23      88 1957.14
   101.6 1956.35     110 1952.87   122.3 1949.19   130.41944.894   138.4 1943.93
   147.8 1944.25  149.661944.927   156.6 1946.84   169.3 1946.21   190.4 1943.92
   208.6 1947.26   302.1 1947.55   359.6 1949.47   371.4 1953.89   380.8 1955.24
   393.3 1959.86   401.8 1961.15   410.3 1963.36     423 1970.32   427.2 1970.97
   444.1 1970.29   448.4 1971.01   452.6 1974.29     461 1982.27   478.7 1991.63
#Mann= 7 ,-1,0
       0      .1       0      60     .06       0   130.4    .045       0
  149.66     .06       0     160      .1       0     370     .06       0
     470      .1       0
Bank Sta=130.4,149.66
XS Rating Curve= 0 ,0
Exp/Cntr(USF)=0,0
Exp/Cntr=0.3,0.1

Type RM Length L Ch R = 1 ,3562    ,227.4,227.4,227.4
XS GIS Cut Line= 2
2301689.68686091734710.9886104072301422.77969957734312.619712873
#Sta/Elev= 30
       0 1997.76    64.8 1973.39    81.8 1968.49    88.9 1965.09   100.4 1963.25
   127.4 1953.74   141.8 1952.13   163.8 1946.82  168.971944.306   170.7 1943.69
   181.1  1943.5     1881944.186     190  1944.8   198.4 1945.94   218.3 1945.26
   232.7 1945.95   242.9 1945.27   252.5 1946.11   284.9 1946.47   334.4  1949.2
   358.5 1955.25   383.6 1958.28     397 1962.18   406.6 1967.48   411.4 1968.63
   430.7 1968.13   435.5 1968.67   445.1 1974.62   459.6 1981.65   479.5 1993.24
#Mann= 7 ,-1,0
       0      .1       0      70     .06       0  168.97    .045       0
     188     .06       0     190      .1       0     310     .06       0
  479.52      .1       0
Bank Sta=168.97,188
XS Rating Curve= 0 ,0
Exp/Cntr(USF)=0,0
Exp/Cntr=0.3,0.1

Type RM Length L Ch R = 1 ,3334    ,258,258,258
XS GIS Cut Line= 2
2301803.88594487734660.5285500522301600.71780713734219.666970115
#Sta/Elev= 30
       0 1999.82    43.3  1983.7    56.5 1978.13    69.8 1973.76    86.7 1966.51
   116.9 1958.11   122.6 1954.56   125.9 1953.47     150 1952.55   156.1 1951.44
   159.1 1949.95   166.6 1943.71   175.5 1942.66   183.2 1942.92   186.2 1943.78
   193.1 1945.57   211.7 1945.54   228.7 1946.35     290 1944.97   300.8  1946.7
   315.9 1947.69   342.4 1952.63   358.1 1956.61   367.1 1961.42     372 1962.69
   404.5 1964.89   426.5 1965.15   430.9 1967.48   439.7  1974.7   485.4 1996.14
#Mann= 7 ,-1,0
       0      .1       0      10     .06       0     120     .05       0
   166.6    .045       0   186.2     .05       0     330     .07       0
     440      .1       0
Bank Sta=166.6,186.2
XS Rating Curve= 0 ,0
Exp/Cntr(USF)=0,0
Exp/Cntr=0.3,0.1