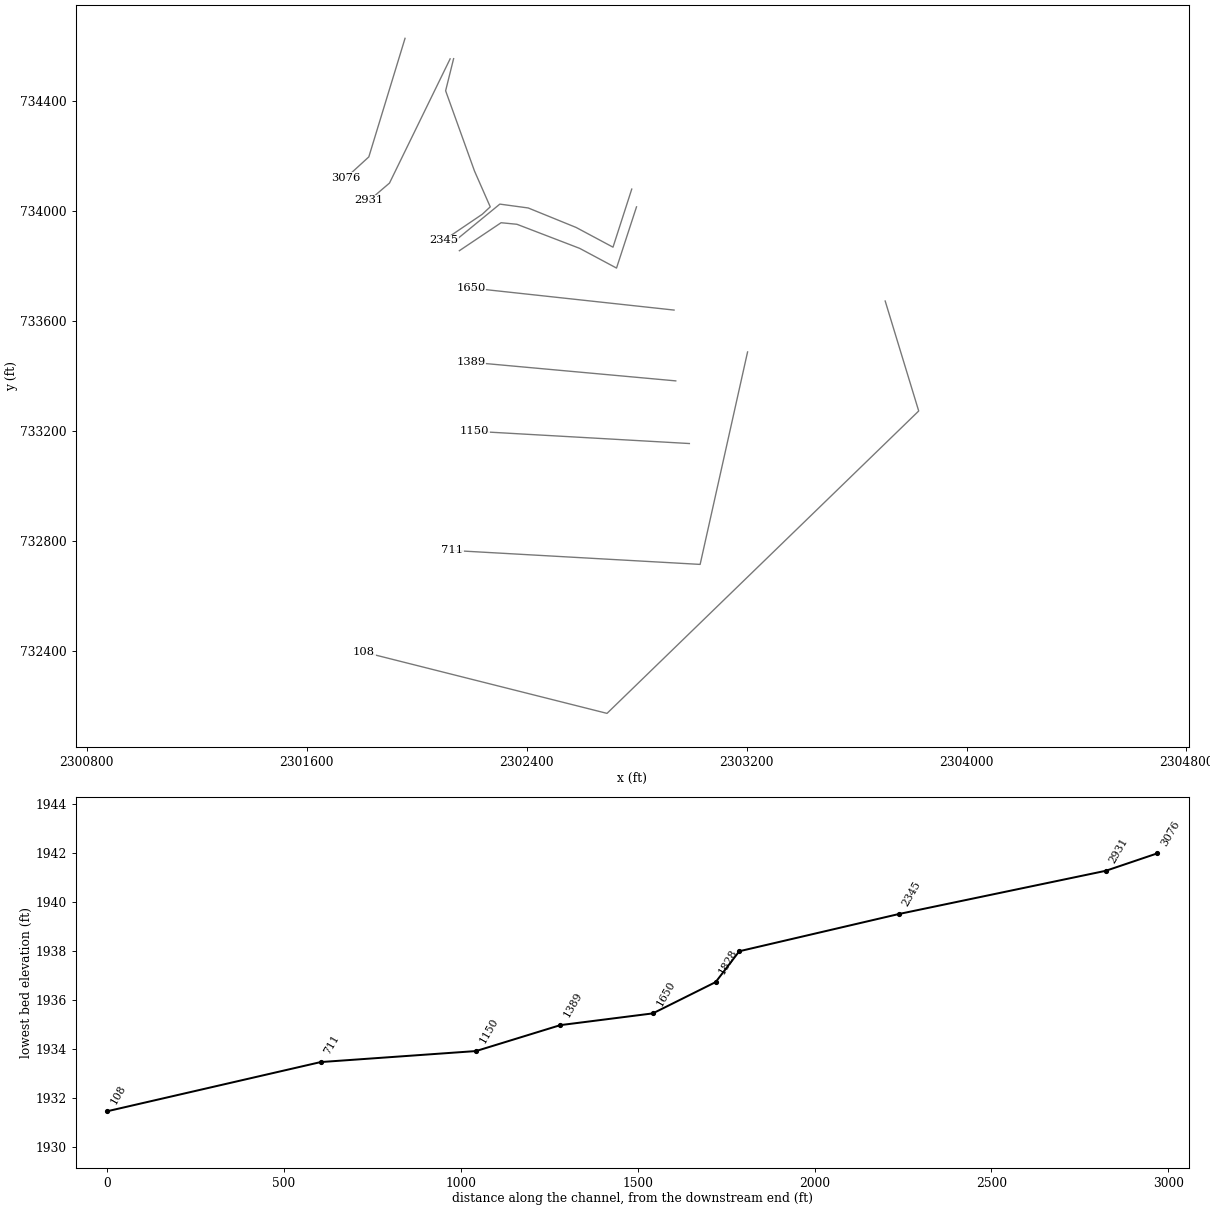
HEC-RAS study DAVISLCK.prj: DAVISLCK

--- DAVISLCK.g01 (geometry) --- (continued)

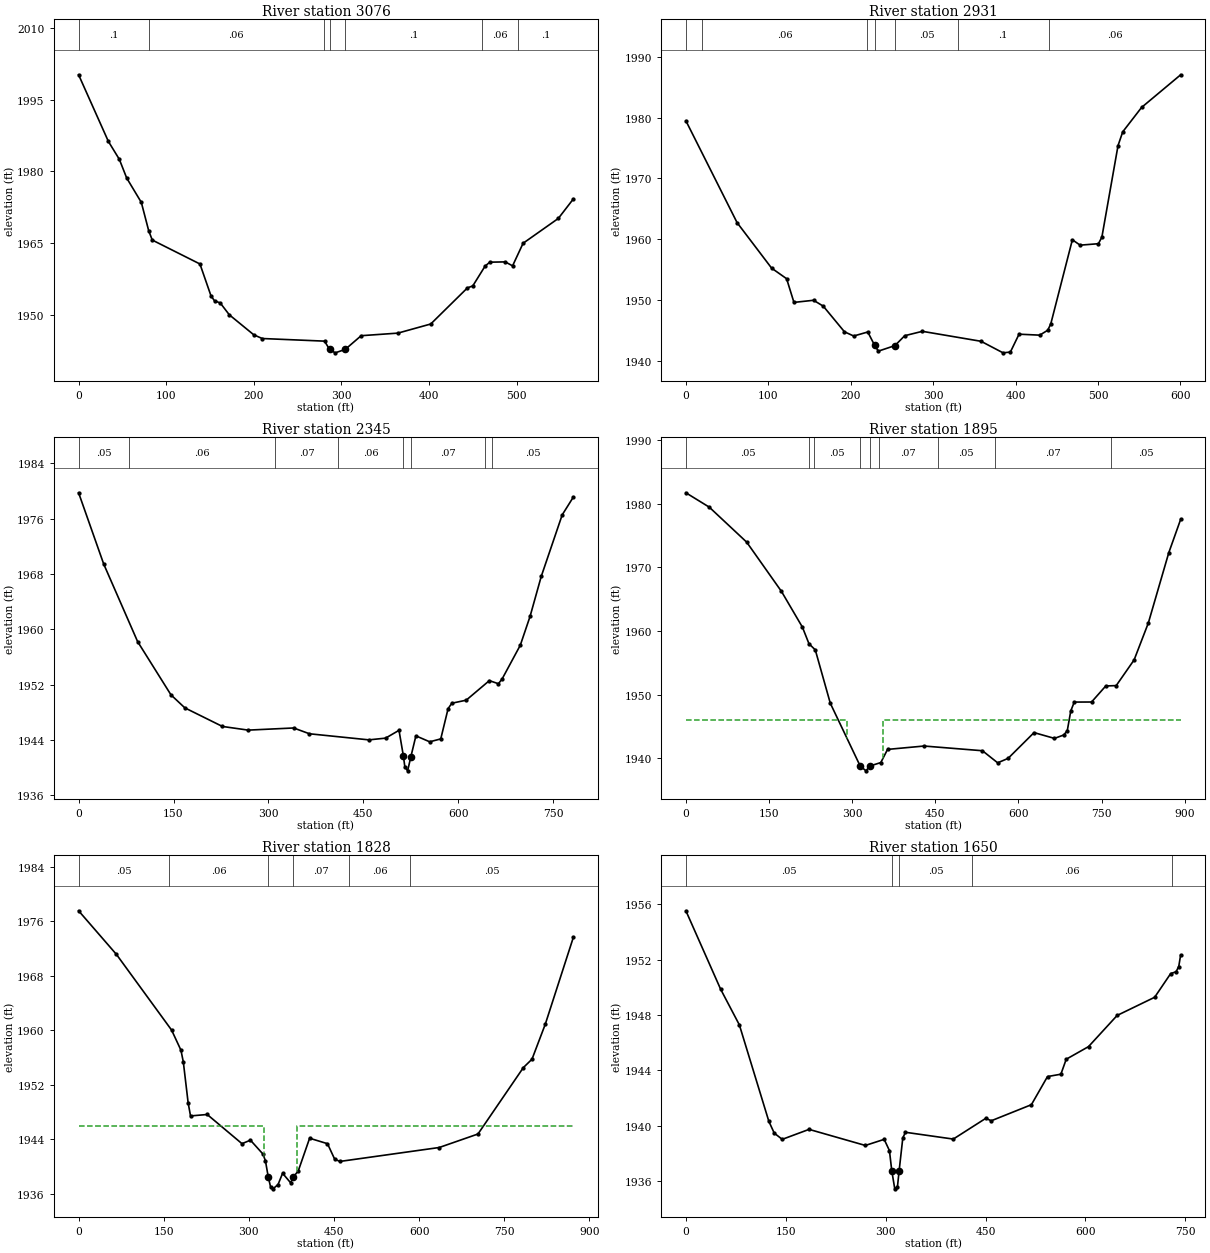
Type RM Length L Ch R = 1 ,3076    ,145.1,145.1,145.1
XS GIS Cut Line= 3
2301957.44152035734629.6558245992301825.71112418734198.395599041
2301741.81140757734121.552867941
#Sta/Elev= 30
       0 2000.24      34 1986.28    46.5 1982.53    54.9 1978.61    71.6 1973.51
      80 1967.58    84.1 1965.62   138.5 1960.61   151.1 1953.94   155.2 1952.88
   161.6 1952.46     172 1949.97     200 1945.77   209.6    1945   280.7 1944.45
   286.5  1942.7   292.9    1942  304.331942.723   322.5 1945.59   364.4 1946.13
   401.9 1948.04   443.8 1955.61   449.9 1956.02   463.9 1960.16   469.3 1960.99
   486.9 1961.05   495.3 1960.22   507.3 1964.95   547.5 1970.15   564.7 1974.24
#Mann= 7 ,-1,0
       0      .1       0      80     .06       0     280      .1       0
   286.5    .045       0  304.33      .1       0  460.93     .06       0
  500.93      .1       0
Bank Sta=286.5,304.33
XS Rating Curve= 0 ,0
Exp/Cntr(USF)=0,0
Exp/Cntr=0.3,0.1

Type RM Length L Ch R = 1 ,2931    ,586,586,586
XS GIS Cut Line= 3
2302121.46091855734554.9886132532301900.96373376 734103.23828345
2301826.74760815734039.778118073
#Sta/Elev= 30
       0 1979.48    62.1 1962.72     104 1955.23   122.2 1953.49   131.1 1949.59
   154.9 1949.94   166.7 1948.97   192.4 1944.75   203.6 1944.06   220.7 1944.72
     229 1942.52   233.5 1941.57   253.6 1942.48   265.5 1944.11   286.9 1944.83
   358.1 1943.19   384.8 1941.29   393.7 1941.42   404.2 1944.36   429.3  1944.2
     439 1945.01   442.7 1946.05   468.9  1959.9   478.3 1959.01   500.5 1959.25
   504.7 1960.33   524.3  1975.4     530 1977.66   552.9 1981.68   600.3 1987.05
#Mann= 7 ,-1,0
       0     .05       0      20     .06       0     220     .05       0
     229    .045       0   253.6     .05       0     330      .1       0
     440     .06       0
Bank Sta=229,253.6
XS Rating Curve= 0 ,0
Exp/Cntr(USF)=0,0
Exp/Cntr=0.3,0.1

Type RM Length L Ch R = 1 ,2345    ,450.6,450.6,450.6
BEGIN DESCRIPTION:
Structure
END DESCRIPTION:
XS GIS Cut Line= 6
2302134.14062744 734555.72895231 2302105.0829481734438.921854772
2302210.15019635734146.8483983232302267.40274696734016.672663242
 2302238.3693594 733989.712178322302098.05194532733894.757221235
#Sta/Elev= 30
       0 1979.74    39.7 1969.43    93.3 1958.21     146 1950.51   167.9 1948.63
   227.3 1945.94     268 1945.41   339.9 1945.72   364.9 1944.88   458.8    1944
   485.2 1944.25   506.4 1945.38  513.241941.713   515.6 1940.12     520 1939.52
   525.2 1941.58   533.1 1944.58   554.9 1943.72   572.4 1944.14     584 1948.52
   589.9  1949.3   612.6 1949.74   649.2 1952.57   663.5 1952.12   669.3  1952.8
   698.1 1957.69   713.5 1961.85   731.2 1967.64   764.3 1976.54     782 1979.13
#Mann= 8 ,-1,0
       0     .05       0      80     .06       0  310.37     .07       0
  410.37     .06       0  513.24    .045       0   525.2     .07       0
  642.59     .06       0  652.59     .05       0
Bank Sta=513.24,525.2
XS Rating Curve= 0 ,0
Exp/Cntr(USF)=0,0
Exp/Cntr=0.3,0.1

Type RM Length L Ch R = 1 ,1895    ,66.7,66.7,66.7
BEGIN DESCRIPTION:
Structure XS 3 23.7ft
END DESCRIPTION:
XS GIS Cut Line= 6
2302782.14142298734081.3169224112302713.95415442733869.982706981
2302579.83662558733941.6891085372302405.48576725734012.609109793
2302302.29286551734026.6373863042302127.57675445733883.476208348
#Sta/Elev= 30
       0 1981.71    42.2 1979.45   109.7 1973.95   172.5  1966.2   210.3 1960.58
   222.1 1957.98   233.5 1957.01   260.6 1948.62   314.6 1938.74   325.1    1938
   331.7 1938.75   351.7  1939.3   363.9 1941.37   429.8  1941.9   535.1 1941.16
   562.6 1939.26   581.4 1939.96   628.2 1944.01   665.1  1943.1   681.9 1943.64
   688.2 1944.32   694.5 1947.42   700.8 1948.81     732 1948.82   757.6 1951.34
   776.5  1951.4   808.8 1955.44   834.4 1961.23   871.3 1972.28   892.8 1977.54
#Mann= 9 ,-1,0
       0     .05       0  222.06     .06       0  232.06     .05       0
   314.6    .045       0   331.7     .05       0  348.79     .07       0
  454.31     .05       0  557.53     .07       0  766.96     .05       0
#XS Ineff= 2 , 0
           290.9    1946   355.4            1946
Permanent Ineff=
       F       F
Bank Sta=314.6,331.7
XS Rating Curve= 0 ,0
Exp/Cntr(USF)=0,0
Exp/Cntr=0.3,0.1

Type RM Length L Ch R = 1 ,1828    ,177.7,177.7,177.7
BEGIN DESCRIPTION:
Structure XS 2 20.4ft 6.8
END DESCRIPTION:
XS GIS Cut Line= 6
2302799.44981092734016.6091608462302726.74760253733793.987595838
2302592.63007369733865.6939973942302364.37328819733953.269614048
2302306.80780534733958.9132888372302155.04375701733857.145435348
#Sta/Elev= 30
       0 1977.51    66.7 1971.11   163.9 1960.01   180.3 1957.07   184.5 1955.35
     193 1949.35   197.2 1947.43   226.6 1947.64   287.9 1943.36   302.7 1943.88
   324.8 1941.84   329.2 1940.84  334.131938.478   338.1 1937.07   342.5 1936.74
   351.4 1937.37   359.4 1939.02   373.6 1937.62   378.1 1938.48   386.9 1939.34
     407 1944.16   438.5 1943.36   451.2 1941.08   460.5 1940.76   635.3  1942.8
   703.6 1944.78   783.6 1954.52   798.8 1955.75   822.2 1960.88   871.7 1973.63
#Mann= 6 ,-1,0
       0     .05       0     160     .06       0  334.13    .045       0
   378.1     .07       0  476.44     .06       0   584.7     .05       0
#XS Ineff= 2 , 0
          327.33    1946   384.9            1946
Permanent Ineff=
       F       F
Bank Sta=334.13,378.1
XS Rating Curve= 0 ,0
Exp/Cntr(USF)=0,0
Exp/Cntr=0.3,0.1

Type RM Length L Ch R = 1 ,1650    ,261.6,261.6,261.6
XS GIS Cut Line= 2
2302936.05447163733641.2006266382302197.24983686733721.404887615
#Sta/Elev= 30
       0 1955.52    52.2 1949.86    80.3 1947.29   124.6 1940.33   132.7 1939.48
   144.7 1939.03     185 1939.75   269.5 1938.59   297.8 1939.03   305.7 1938.22
  309.191936.774   313.7 1935.46   317.7 1935.59   320.3 1936.78   325.8 1939.14
   329.8 1939.54   401.6 1939.05   450.5 1940.55   458.6 1940.37   518.9 1941.53
   543.1 1943.56   563.2 1943.73   571.2 1944.81   604.7 1945.72   647.7 1947.97
     704 1949.28   728.1 1950.99   736.2 1951.12   740.2  1951.5   743.1 1952.34
#Mann= 5 ,-1,0
       0     .05       0  309.19    .045       0   320.3     .05       0
     430     .06       0     730     .05       0
Bank Sta=309.19,320.3
XS Rating Curve= 0 ,0
Exp/Cntr(USF)=0,0
Exp/Cntr=0.3,0.1

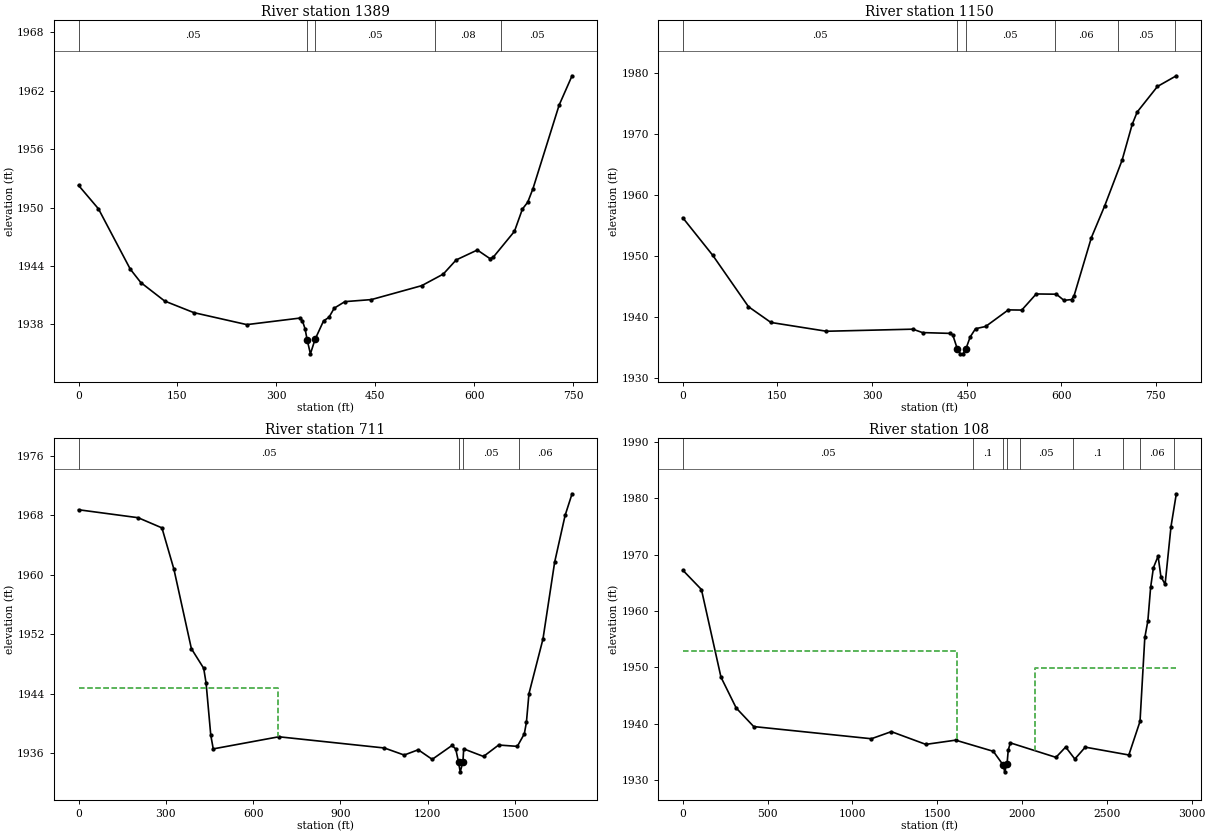
Type RM Length L Ch R = 1 ,1389    ,238.4,238.4,238.4
XS GIS Cut Line= 2
2302942.22403016733383.6215577312302197.24983686733451.486701634
#Sta/Elev= 30
       0 1952.28    30.2 1949.87    78.4 1943.68    94.4  1942.3   130.6  1940.4
   174.8 1939.21   255.1 1937.98   335.4 1938.65   339.4 1938.37   343.5 1937.52
  346.451936.443   351.5 1934.98   358.5 1936.46   371.4 1938.36   379.6 1938.73
   387.6 1939.67   403.7 1940.34   443.9 1940.55   520.2 1941.98   552.9 1943.17
   572.4 1944.62   604.5 1945.64   623.6 1944.76   628.6  1944.9   660.8 1947.56
   672.8 1949.84   680.9 1950.55   688.9 1951.95   728.5 1960.52   748.1 1963.53
#Mann= 5 ,-1,0
       0     .05       0  346.45    .045       0   358.5     .05       0
     540     .08       0     640     .05       0
Bank Sta=346.45,358.5
XS Rating Curve= 0 ,0
Exp/Cntr(USF)=0,0
Exp/Cntr=0.3,0.1

Type RM Length L Ch R = 1 ,1150    ,439.1,439.1,439.1
XS GIS Cut Line= 2
2302991.72799802733155.7182045552302210.25058337 733200.27612732
#Sta/Elev= 30
       0 1956.21    47.6 1950.05   104.2 1941.64   139.8 1939.06   227.9 1937.62
   364.8 1937.96   380.2  1937.4   424.2 1937.27   428.2 1937.02   435.6 1934.66
   440.3 1933.92   444.3 1933.93  448.971934.726   455.8 1936.69   464.3 1938.04
   480.3  1938.4   516.3 1941.12   537.6 1941.09   560.5 1943.73   592.5 1943.69
   604.5 1942.68   616.6 1942.81   620.6 1943.45     648 1952.96   669.3 1958.21
   696.7 1965.64   712.7  1971.5   720.7 1973.54   752.8 1977.72   782.7 1979.47
#Mann= 6 ,-1,0
       0     .05       0   435.6    .045       0  448.97     .05       0
     590     .06       0     690     .05       0     780     .03       0
Bank Sta=435.6,448.97
XS Rating Curve= 0 ,0
Exp/Cntr(USF)=0,0
Exp/Cntr=0.3,0.1

Type RM Length L Ch R = 1 ,711     ,603.5,603.5,603.5
XS GIS Cut Line= 3
2303203.46672225733488.9225807112303030.87818873732716.041403505
2302128.35029486 732766.83126682
#Sta/Elev= 30
       0 1968.75   204.7 1967.68   286.6 1966.31   327.8 1960.74   387.8 1950.05
   430.1 1947.41   438.3 1945.43   454.4 1938.41   462.9 1936.56   688.3 1938.19
    1051 1936.68  1119.1 1935.73  1167.3 1936.44  1215.3 1935.15  1283.4 1937.02
  1296.2 1936.54 1305.77 1934.79  1311.5 1933.47 1320.89 1934.79  1323.5 1936.56
  1391.6 1935.54  1443.6 1937.08  1507.8  1936.9  1531.8 1938.58    1539 1940.12
  1547.8    1944  1595.9 1951.34    1636 1961.68    1672 1967.99  1695.9  1970.9
#Mann= 4 ,-1,0
       0     .05       0 1305.77    .045       0 1320.89     .05       0
 1511.92     .06       0
#XS Ineff= 2 , 0
          686.83 1944.69
Permanent Ineff=
       F       F
Bank Sta=1305.77,1320.89
XS Rating Curve= 0 ,0
Exp/Cntr(USF)=0,0
Exp/Cntr=0.3,0.1

Type RM Length L Ch R = 1 ,108     ,,,
XS GIS Cut Line= 4
2303704.03013145733674.1386319182303825.95454378733274.094996105
2302692.18189979 732174.143668352301808.09385306732396.811317119
#Sta/Elev= 30
       0 1967.23   109.9  1963.8   225.2 1948.25     315 1942.78   418.2 1939.49
  1111.8 1937.33  1229.5 1938.59  1432.8 1936.33  1608.6 1937.08  1830.7  1935.1
1890.2021932.609  1897.6 1931.461911.5781932.833  1918.8 1935.33    1931  1936.6
    2200 1934.03  2257.4 1935.86  2311.4 1933.73  2372.7 1935.84  2629.7 1934.45
  2695.6 1940.41  2723.9  1955.3  2741.8 1958.21  2758.2  1964.2  2774.7 1967.67
  2802.2 1969.72  2818.7  1966.1  2843.5 1964.72  2878.3 1974.97  2909.6 1980.78
#Mann= 9 ,-1,0
       0     .05       0 1708.21      .1       01890.202    .045       0
1911.578      .1       0 1988.21     .05       0 2297.87      .1       0
 2597.87     .08       0 2697.87     .06       0 2897.87      .1       0
#XS Ineff= 2 , 0
         1614.44  1952.9 2076.53         1949.79
Permanent Ineff=
       F       F
Bank Sta=1890.202,1911.578
XS Rating Curve= 0 ,0
Exp/Cntr(USF)=0,0
Exp/Cntr=0.3,0.1
LCMann Table=0

Chan Stop Cuts=-1
Use User Specified Reach Order=0
Composite Channel Slope=5